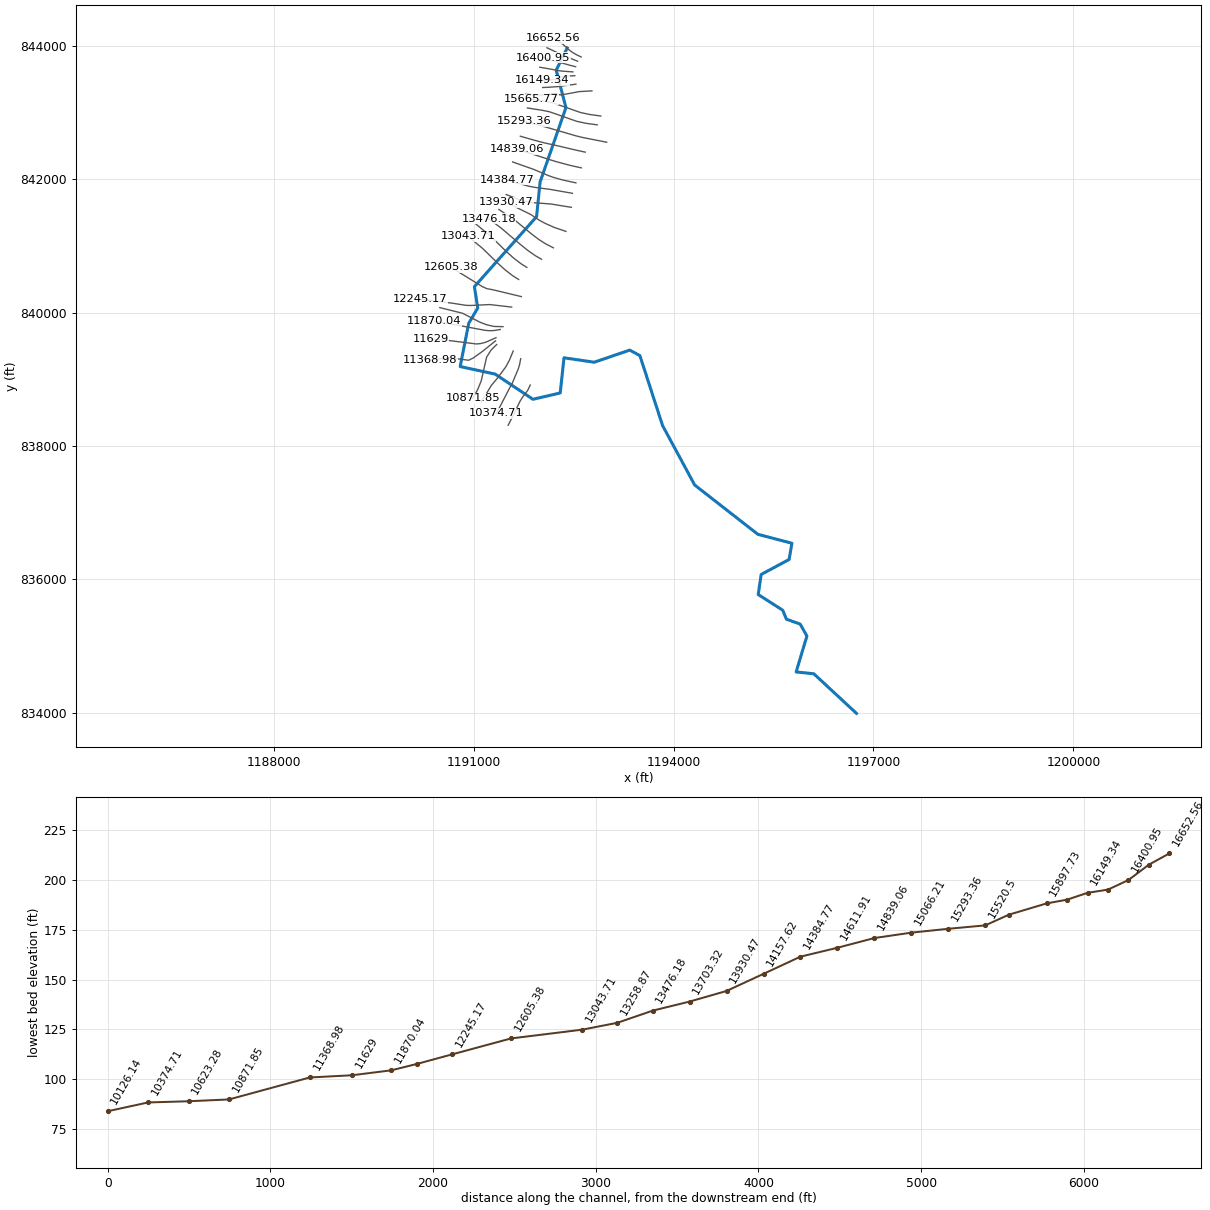
--- 109_ras.prj (project) ---

Proj Title=109
Current Plan=p01
Default Exp/Contr=0.3,0.1
English Units
Geom File=g01
Flow File=f01
Plan File=p01
Y Axis Title=Elevation
X Axis Title(PF)=Main Channel Distance
X Axis Title(XS)=Station
BEGIN DESCRIPTION:
RFD model 109 exported to HEC-RAS
END DESCRIPTION:

--- 109_ras.p01 (plan) ---

Plan Title=Plan 01
Program Version=4.10
Short Identifier=Plan 01
Geom File=g01
Flow File=f01
Subcritical Flow
Calc Critical at every XS
Secant Critical Depth

--- 109_ras.f01 (steady flow) ---

Flow Title=Flow 01
Program Version=5.01
Number of Profiles= 5
Profile Names=10yr,25yr,50yr,100yr,500yr
River Rch & RM=109,65,16652.56
   357.6     651  946.94 1314.92 2487.04
River Rch & RM=109,65,16526.76
  367.85  670.07  975.25  1355.1 2567.45
River Rch & RM=109,65,16400.95
  369.65  673.43  980.25  1362.2 2581.66
River Rch & RM=109,65,16275.15
  406.35  741.82 1081.95 1506.75 2872.08
River Rch & RM=109,65,16149.34
  417.76  763.12 1113.65 1551.87 2963.07
River Rch & RM=109,65,16023.54
  427.96  782.16 1142.02 1592.28 3044.68
River Rch & RM=109,65,15897.73
  430.96  787.77 1150.37 1604.17 3068.72
River Rch & RM=109,65,15665.77
  454.33  831.45 1215.51 1697.03 3256.79
River Rch & RM=109,65, 15520.5
  477.06  873.99 1279.01 1787.67 3440.93
River Rch & RM=109,65,15293.36
  506.93  929.95 1362.64 1907.18 3684.52
River Rch & RM=109,65,15066.21
  514.69  944.49 1384.39 1938.29 3748.08
River Rch & RM=109,65,14839.06
  652.59 1203.79 1773.28 2496.16 4896.95
River Rch & RM=109,65,14611.91
  656.73 1211.61 1785.04 2513.07 4932.01
River Rch & RM=109,65,14384.77
  658.51 1214.96 1790.07 2520.31 4947.04
River Rch & RM=109,65,14157.62
  772.53 1430.34 2114.48 2987.85 5921.91
River Rch & RM=109,65,13930.47
  777.25 1439.26 2127.94 3007.28 5962.64
River Rch & RM=109,65,13703.32
  787.26 1458.22 2156.55  3048.6 6049.26
River Rch & RM=109,65,13476.18
  797.87 1478.29 2186.85 3092.36 6141.09
River Rch & RM=109,65,13258.87
  808.46 1498.36 2217.15 3136.15 6233.04
River Rch & RM=109,65,13043.71
  832.59 1544.06 2286.19 3235.97 6442.92
River Rch & RM=109,65,12605.38
 1893.55  3575.5 5386.15 7766.9916255.76
River Rch & RM=109,65,12245.17
 3405.43 6513.61 9933.85 14516.631484.94
River Rch & RM=109,65,12026.13
  3420.1 6542.28 9978.4814583.2331637.72
River Rch & RM=109,65,11870.04
 3423.48  6548.9 9988.7814598.6131672.99
River Rch & RM=109,65,   11629
 3442.09 6585.2810045.42 14683.2   31867
River Rch & RM=109,65,11368.98
 3461.27 6622.7710103.7914770.3732067.01
River Rch & RM=109,65,10871.85
 3653.96 6999.7910691.1315648.1734084.72
River Rch & RM=109,65,10623.28
 3662.97 7017.4210718.6215689.2834179.38
River Rch & RM=109,65,10374.71
 3759.76 7206.9711014.1716131.4235198.31
River Rch & RM=109,65,10126.14
 3865.47 7414.1111337.3316615.1636314.93
River Rch & RM=109,65,9791.148
 3875.02 7432.8411366.5616658.9236416.04
River Rch & RM=109,65,9468.388
 3905.37 7492.3311459.4116797.9736737.39
River Rch & RM=109,65,9253.244
  3909.3 7500.0411471.45   1681636779.07
River Rch & RM=109,65,8883.295
 3942.45 7565.03 11572.916967.97 37130.5
River Rch & RM=109,65,8634.726
 3950.31 7580.4511596.9817004.0437213.93
River Rch & RM=109,65,8425.299
 3957.05 7593.6711617.6217034.9637285.45
River Rch & RM=109,65,8137.588
 4229.19 8127.75 12452.118286.0940185.91
River Rch & RM=109,65,7863.016
 4728.93 9110.4613990.4320597.1845572.96
River Rch & RM=109,65,7708.096
 4730.61 9113.76 13995.620604.9645591.16
River Rch & RM=109,65,7486.309
 4754.63 9161.0614069.7320716.48   45852
River Rch & RM=109,65,7264.522
 4764.69 9180.8514100.7620763.1645961.23
River Rch & RM=109,65,7042.735
  4768.6 9188.5514112.8320781.3246003.72
River Rch & RM=109,65,6891.667
 4802.11 9254.5514216.2820936.9746368.01
River Rch & RM=109,65,6733.392
 4823.33 9296.3414281.8121035.5846598.86
River Rch & RM=109,65,6593.095
 4833.94 9317.2414314.5721084.8846714.32
River Rch & RM=109,65,6365.241
 4844.55 9338.1314347.3321134.19 46829.8
River Rch & RM=109,65,6137.387
 4961.75 9569.0714709.5321679.4648107.82
River Rch & RM=109,65,5909.534
 5129.05  9898.915227.1622459.2149938.63
River Rch & RM=109,65, 5681.68
 5132.95  9906.615239.2422477.4249981.42
River Rch & RM=109,65,5449.291
 5146.88 9934.0815282.3822542.4450134.26
River Rch & RM=109,65,5216.902
 5184.2210007.7315398.0222716.7350544.08
River Rch & RM=109,65,4984.513
 5199.8210038.5115446.3522789.5950715.42
River Rch & RM=109,65,4752.123
 5208.73 10056.115473.9722831.2250813.36
River Rch & RM=109,65,4519.734
 5230.4610098.9615541.2922932.7151052.15
River Rch & RM=109,65,4287.345
 5234.3610106.6615553.3722950.9351095.02
River Rch & RM=109,65,3796.581
  5338.510312.1815876.23 23437.852241.39
River Rch & RM=109,65,3115.799
 5374.1210382.5115986.74 23604.552634.23
River Rch & RM=109,65, 2880.74
  5393.610420.9816047.1823695.6952849.17
River Rch & RM=109,65,2614.903
 5399.7310433.0616066.1823724.3552916.74
River Rch & RM=109,65,2479.741
 5404.1810441.85   1608023745.1952965.89
River Rch & RM=109,65,2174.191
  5457.610547.34 16245.823995.3853555.93
River Rch & RM=109,65,1739.991
 5487.0810605.5816337.3524133.5453881.93
River Rch & RM=109,65,1325.405
 5537.6910705.5616494.5424370.8254442.05
River Rch & RM=109,65,676.7098
 5551.0410731.9316536.0124433.4154589.86
River Rch & RM=109,65,470.1806
 5558.8310747.3116560.1924469.93 54676.1
Boundary for River Rch & Prof#=109,65,1
Up Type= 0
Dn Type= 2
Boundary for River Rch & Prof#=109,65,2
Up Type= 0
Dn Type= 2
Boundary for River Rch & Prof#=109,65,2
Up Type= 0
Dn Type= 2
Boundary for River Rch & Prof#=109,65,2
Up Type= 0
Dn Type= 2
Boundary for River Rch & Prof#=109,65,2
Up Type= 0
Dn Type= 2

--- 109_ras.g01 (geometry) ---

Geom Title=109
Program Version=4.10

River Reach=109,65
Reach XY= 30
1192404.87714237843970.029292047 1192240.3440901843635.700273573
1192386.17736438843075.7004347891191998.60680801841959.063027471
1191945.78140157841439.6131974011191012.84435642840389.034601554
1191062.84433246840068.2013615671190927.84436548  839839.8680996
1190799.51105103839190.7016284471191324.51089358839077.368313342
1191891.17738295838699.8684084861192300.34393218838794.035035491
 1192357.0105975839321.5348780161192812.01046199839255.701550961
1193342.84364468 839437.368148581193495.34359756839355.701501653
1193835.34346727838306.5351351051194317.84329972837413.202051699
1195265.34300005836674.0355759861195776.17617944 836539.86893414
1195733.67618483836295.702340856 1195315.3429679 836071.53575252
1195270.34297237835770.7025093881195637.84285763835535.702568173
1195694.50950372 835399.869273351195900.34277451835327.369288787
1196001.17607298835147.3693390791195839.50943822834609.036169469
1196105.34269264834581.5361699011196744.78824759833987.623718455

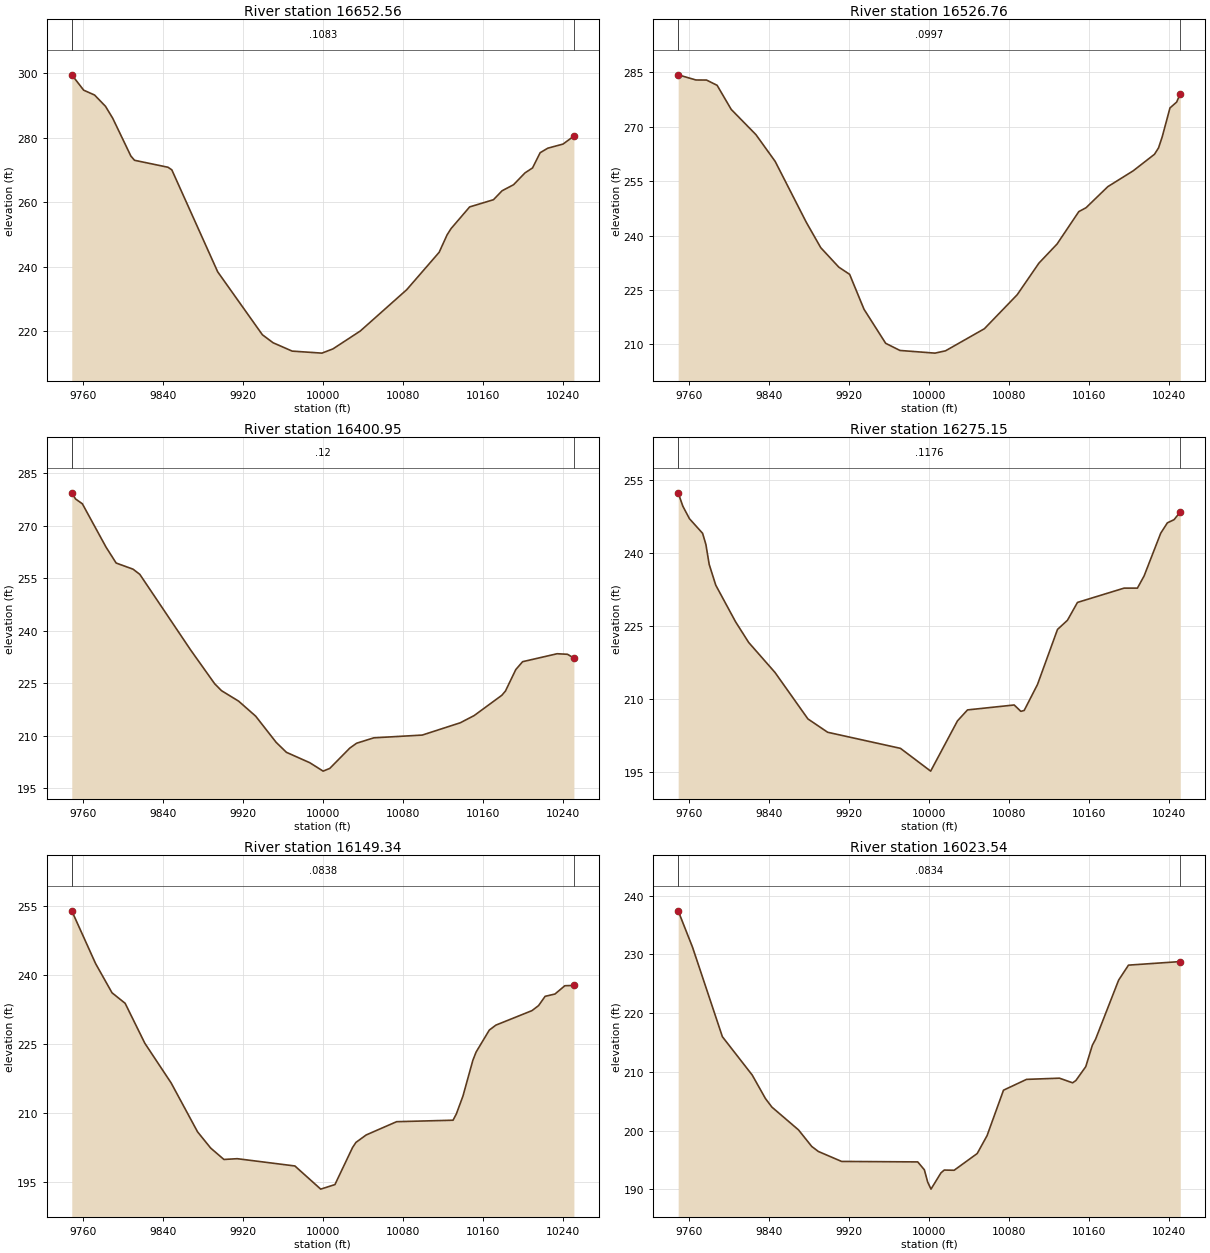
Type RM Length L Ch R = 1 ,16652.56,125.805200,125.805200,125.805200
XS GIS Cut Line= 6
1192614.31720995843835.2494582281192541.36877616843869.726672449
 1192478.1088227843907.5304781531192434.31591666843940.811408673
1192331.65084609844032.0490066241192200.46702069844114.434564073
#Sta/Elev= 30
9749.104  299.519761.019294.74929771.905293.24199782.792289.7557 9790.05286.0384
9808.194274.31579811.822 273.0159845.264270.85529849.086270.0573 9894.95238.4313
9939.611218.92219950.356216.4362  9969.4213.85389999.117213.229810010.17214.5492
10037.47220.090510083.85232.891510116.28244.495710124.21249.902210128.17251.8424
10146.76258.561710170.54260.787810179.17263.570610190.59265.429910202.01269.0937
10209.62270.653710217.23275.373310224.84276.762410240.07 278.04410250.94280.5162
#Mann= 3 , 0 , 0
9749.104  0.1083       09749.104  0.1083       010250.94  0.1083       0
#XS Ineff= 2 , 0
       0                               0
Bank Sta=9749.104,10250.94
Exp/Cntr=0.3,0.1

Type RM Length L Ch R = 1 ,16526.76,125.805200,125.805200,125.805200
XS GIS Cut Line= 6
1192561.01642554843771.5654143761192485.95849839843801.205012951
1192362.35153048843857.4147934131192329.07537951843869.724411783
1192287.71751342843885.8189246951192101.56773479843973.091202938
#Sta/Elev= 30
9749.033 284.2659766.801282.84529777.383282.82739787.965281.37299802.075 274.733
9826.767267.78769845.997 260.417 9877.16243.61469891.576236.64689909.597231.2915
 9920.41229.31229934.826219.67339956.451210.30889970.715208.342610005.72207.6063
10016.28208.242710055.13214.3276 10087.9223.681610109.64232.397510127.76237.6576
 10149.5246.582810156.75247.659110178.49253.458510203.86257.817210225.17262.3825
10229.22264.1479 10232.9267.201110240.62275.134810247.34276.769310250.97279.0936
#Mann= 3 , 0 , 0
9749.033  0.0997       09749.033  0.0997       010250.97  0.0997       0
#XS Ineff= 2 , 0
       0                               0
Bank Sta=9749.033,10250.97
Exp/Cntr=0.3,0.1

Type RM Length L Ch R = 1 ,16400.95,125.805200,125.805200,125.805200
XS GIS Cut Line= 6
1192531.80155093843689.1661835971192438.48708344 843712.10901264
1192319.87573482 843746.308234551192273.82724297843753.451122372
1192251.86543965843758.7005424641192049.69635624843826.375941567
#Sta/Elev= 30
9749.051279.33479752.878277.57089759.635276.20529783.285263.8392 9793.42259.2879
9810.313257.5356 9817.07256.05749867.989234.4194 9891.89 224.8259898.719222.8484
9915.792219.86629932.864215.57739953.351208.09119963.594205.25389987.021  202.27
10000.32199.876810006.94200.650810027.01206.466310033.76207.840510050.95209.3816
10099.39210.170310137.45213.684310151.29215.741610178.97221.538310182.56222.7425
10192.89228.870910199.72231.123510234.23233.391610244.57233.236410250.98232.1578
#Mann= 3 , 0 , 0
9749.051    0.12       09749.051    0.12       010250.98    0.12       0
#XS Ineff= 2 , 0
       0                               0
Bank Sta=9749.051,10250.98
Exp/Cntr=0.3,0.1

Type RM Length L Ch R = 1 ,16275.15,125.805300,125.805300,125.805300
XS GIS Cut Line= 6
1192490.11203583843610.879875472 1192345.6126715843621.425554582
1192294.73280633843626.849681112  1192248.058955843634.578816965
1192194.71175245843646.0869714191191993.70681487843680.753038763
#Sta/Elev= 30
9749.015252.44469753.705249.68139760.284247.11429773.442244.09669776.732241.8037
9780.021237.6956  9786.6233.40749806.338225.88199819.496221.60419845.812215.4177
9878.708205.84239898.459203.09039971.252199.773910001.42195.081310028.21205.4341
10038.26207.700610084.92208.715910091.58207.4025 10094.9207.584410108.22212.9426
 10128.2224.281610138.18226.181810148.17229.853410194.78232.8014 10208.1232.8034
10214.76235.3001 10231.4 244.12210238.06246.258710244.72246.908810250.98 248.513
#Mann= 3 , 0 , 0
9749.015  0.1176       09749.015  0.1176       010250.98  0.1176       0
#XS Ineff= 2 , 0
       0                               0
Bank Sta=9749.015,10250.98
Exp/Cntr=0.3,0.1

Type RM Length L Ch R = 1 ,16149.34,125.805200,125.805200,125.805200
XS GIS Cut Line= 6
1192519.07596401 843553.947123531192369.07562078 843546.20318315
1192309.21135447843533.5484777431192249.43976977843507.328771944
1192197.33816737843493.9961958121192026.89942933843482.012398031
#Sta/Elev= 30
9749.074253.8544 9772.88242.41039789.289236.07469802.415233.78999822.106225.1211
  9848.4216.5086 9874.76205.9127 9887.94202.37389901.138199.90879914.453200.0746
9972.078198.49699997.878193.472210012.07194.453210029.69202.491510033.12203.6133
10043.39205.234710073.77 208.10510130.16208.423210133.46209.798210140.05 213.667
10149.94221.418710153.24 223.23410166.38227.980210172.95229.054110209.05 232.204
10215.61233.286410222.18235.302410232.03 235.80410241.87237.600310250.94237.6732
#Mann= 3 , 0 , 0
9749.074  0.0838       09749.074  0.0838       010250.94  0.0838       0
#XS Ineff= 2 , 0
       0                               0
Bank Sta=9749.074,10250.94
Exp/Cntr=0.3,0.1

Type RM Length L Ch R = 1 ,16023.54,125.805200,125.805200,125.805200
XS GIS Cut Line= 6
1192535.79885091843426.6849727961192288.02882122843393.483834008
1192286.05010294843393.1928460831192261.07916138843390.104442445
1192123.92255098843380.1179609041192036.69694832843376.365586666
#Sta/Elev= 30
9749.015237.39459763.418231.17859793.209215.97549823.001 209.4589836.241205.4545
9842.731203.99239869.343200.11129882.584197.29059889.204196.44229912.375194.7516
9988.509194.66849995.129193.32879998.439191.245410001.75190.037310011.67192.7931
10014.98193.281310024.89193.247510047.93196.091510057.79199.132210074.24206.8751
10097.27208.712610130.16208.918810143.32208.128910146.61208.521410156.48210.8812
10163.06214.520110166.34215.570310189.33225.601410199.18228.153410250.99228.7597
#Mann= 3 , 0 , 0
9749.015  0.0834       09749.015  0.0834       010250.99  0.0834       0
#XS Ineff= 2 , 0
       0                               0
Bank Sta=9749.015,10250.99
Exp/Cntr=0.3,0.1

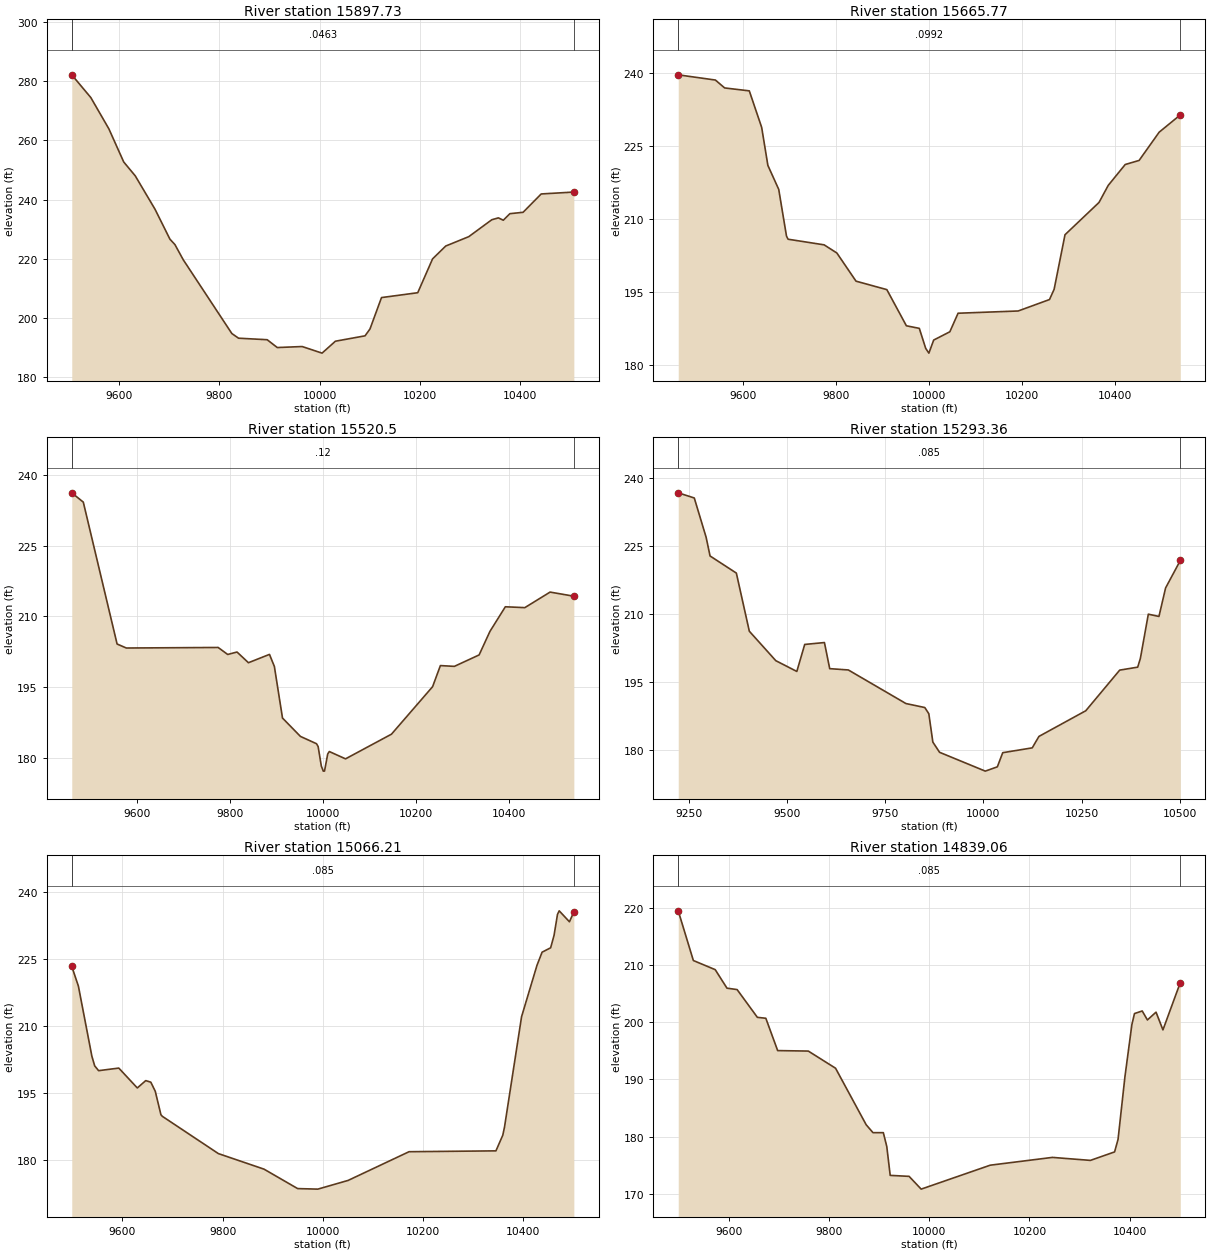
Type RM Length L Ch R = 1 ,15897.73,231.959500,231.959500,231.959500
XS GIS Cut Line= 6
1192776.00289588843326.4239197821192586.04815233843315.365898768
  1192321.782599843265.9368183721192226.31590409843274.514752106
1191966.43821281843262.3615646391191780.83797127843274.729431179
#Sta/Elev= 30
 9505.27282.15239543.229274.48389579.332263.90519608.899252.73059631.955248.0315
 9671.48236.72879701.165226.63849711.121224.81649727.715219.68959824.635194.7894
 9838.07193.20569895.168192.69139915.321190.05069965.036 190.38810004.66188.1639
10031.27192.1839 10090.4 194.00410100.26196.305310123.28206.9243 10195.6208.5647
10225.18219.997110251.44224.332810297.38227.498710343.33233.211410356.47233.8466
10366.32233.049510379.45235.259210405.72235.719510441.92241.920410507.04242.5598
#Mann= 3 , 0 , 0
 9505.27  0.0463       0 9505.27  0.0463       010507.04  0.0463       0
#XS Ineff= 2 , 0
       0                               0
Bank Sta=9505.27,10507.04
Exp/Cntr=0.3,0.1

Type RM Length L Ch R = 1 ,15665.77,145.267600,145.267600,145.267600
XS GIS Cut Line= 6
1192909.32837397842949.2533183041192741.69220178842972.209459269
1192605.65458753843001.4174045181192193.61190657843145.389706328
1192083.06156535843167.8040856621191863.02635479843202.147551274
#Sta/Elev= 30
9459.688239.54959539.688238.48029559.555236.86369612.668236.26229639.285228.7795
9652.642220.98959676.017216.07289692.713206.50479696.083205.86139773.719204.7092
 9801.17203.03379842.346197.26679908.711 195.531 9950.78188.12189978.581187.5952
9992.344183.49419999.224182.518210009.54185.195610044.33186.892110062.04190.6945
10191.36191.153410258.81193.497410268.82195.602710292.19206.777810365.38213.3917
 10385.3216.897810421.83221.172310451.71222.005610494.88227.7943 10540.4231.3389
#Mann= 3 , 0 , 0
9459.688  0.0992       09459.688  0.0992       0 10540.4  0.0992       0
#XS Ineff= 2 , 0
       0                               0
Bank Sta=9459.688,10540.4
Exp/Cntr=0.3,0.1

Type RM Length L Ch R = 1 , 15520.5,227.147600,227.147600,227.147600
XS GIS Cut Line= 6
1192854.56403079842816.719198099 1192686.9278586842839.675339064
1192550.89024436842868.8832843141192138.84756339843012.855586124
1192028.29722217843035.2699654571191808.26201161 843069.61343107
#Sta/Elev= 30
9459.636236.17929484.462 234.2069557.206204.11339577.123203.26569774.723203.3818
9795.312201.89779815.346202.41599839.919200.14649885.199201.91359895.716199.3651
9913.244 188.4129951.807184.5195 9986.47182.96849989.911 182.3749996.792178.2457
   10001177.155710003.66177.164110010.54180.782110013.99 181.31110048.91179.7576
10147.84184.995310236.34195.067410253.11199.538610283.15199.373910336.46201.7975
 10359.7206.780710392.91212.012310434.87211.830310489.21215.126910540.35214.2554
#Mann= 3 , 0 , 0
9459.636    0.12       09459.636    0.12       010540.35    0.12       0
#XS Ineff= 2 , 0
       0                10056.48       0
Bank Sta=9459.636,10540.35
Exp/Cntr=0.3,0.1

Type RM Length L Ch R = 1 ,15293.36,227.147500,227.147500,227.147500
XS GIS Cut Line= 6
1192997.89544338842555.5655363051192623.68986201842629.777627721
1192530.60202473842653.2810498181192046.17031699842794.457865447
  1191925.322496842826.4332620051191760.11061326842867.129925996
#Sta/Elev= 30
9223.749236.66719264.549235.53589294.651226.91199304.686222.7807 9371.58219.0147
9404.613206.22699471.922199.75129525.438197.38029545.506203.32049595.677203.7362
  9609.1197.99529656.474197.70789803.069190.31869850.956189.44559861.218188.0823
9871.479181.84289888.582179.596710004.87175.456910035.58176.402610049.23179.5109
10124.31180.575110141.38183.092710260.52188.7358 10346.8197.6722 10392.6198.3233
10399.36200.222310419.63 209.97710446.67 209.47610463.56215.7426   10501221.7833
#Mann= 3 , 0 , 0
9223.749   0.085       09223.749   0.085       0   10501   0.085       0
#XS Ineff= 2 , 0
       0                10100.05       0
Bank Sta=9223.749,10501
Exp/Cntr=0.3,0.1

Type RM Length L Ch R = 1 ,15066.21,227.147600,227.147600,227.147600
XS GIS Cut Line= 6
1192675.56596686842407.1333960971192541.59832838842436.317233903
1192290.74938153842495.6475908961192061.98932024842546.265133515
1191921.56030679842583.2921527651191702.72550815842645.758255536
#Sta/Elev= 30
9499.007223.33479512.277218.8899 9539.14203.23599544.727201.08449552.571 200.003
9592.864200.5836  9629.8196.13859646.631197.77929656.745197.43239665.636195.3987
9676.973190.1451 9679.89189.78549791.599181.45859882.625177.98299949.807173.6322
9990.086173.5133 10050.6175.463410172.07181.878710345.51182.071110359.15185.5581
10362.57187.352110396.68212.074610427.39223.551710437.63226.499510454.69227.4857
10461.51230.271110468.33234.943310471.75235.749110492.22233.296210500.99235.5104
#Mann= 3 , 0 , 0
9499.007   0.085       09499.007   0.085       010500.99   0.085       0
#XS Ineff= 2 , 0
       0                10146.25       0
Bank Sta=9499.007,10500.99
Exp/Cntr=0.3,0.1

Type RM Length L Ch R = 1 ,14839.06,227.147500,227.147500,227.147500
XS GIS Cut Line= 6
1192616.67485464842171.7291085441192518.06275512842192.723799132
1192421.47020856 842215.611822761192243.55683274842263.584068278
1192154.84393971842290.6439617721191655.20789559842451.448026522
#Sta/Elev= 30
9499.019219.49629529.215210.80359572.822209.20439596.302205.96539616.514205.7202
9656.974200.86229673.833200.70079697.435195.04479758.586194.96119812.954191.9631
9874.118182.06819887.751 180.6879908.331180.68739915.191178.27859922.051173.2141
9959.782173.04229983.829170.809510121.69174.997210245.77176.360510321.59175.8357
10369.84177.319910376.74179.507910390.52190.489210404.31199.572610409.54201.5265
10424.99201.977210435.33 200.40410452.56201.772110466.35198.6675   10501206.9466
#Mann= 3 , 0 , 0
9499.019   0.085       09499.019   0.085       0   10501   0.085       0
#XS Ineff= 2 , 0
       0                10130.11       0
Bank Sta=9499.019,10501
Exp/Cntr=0.3,0.1

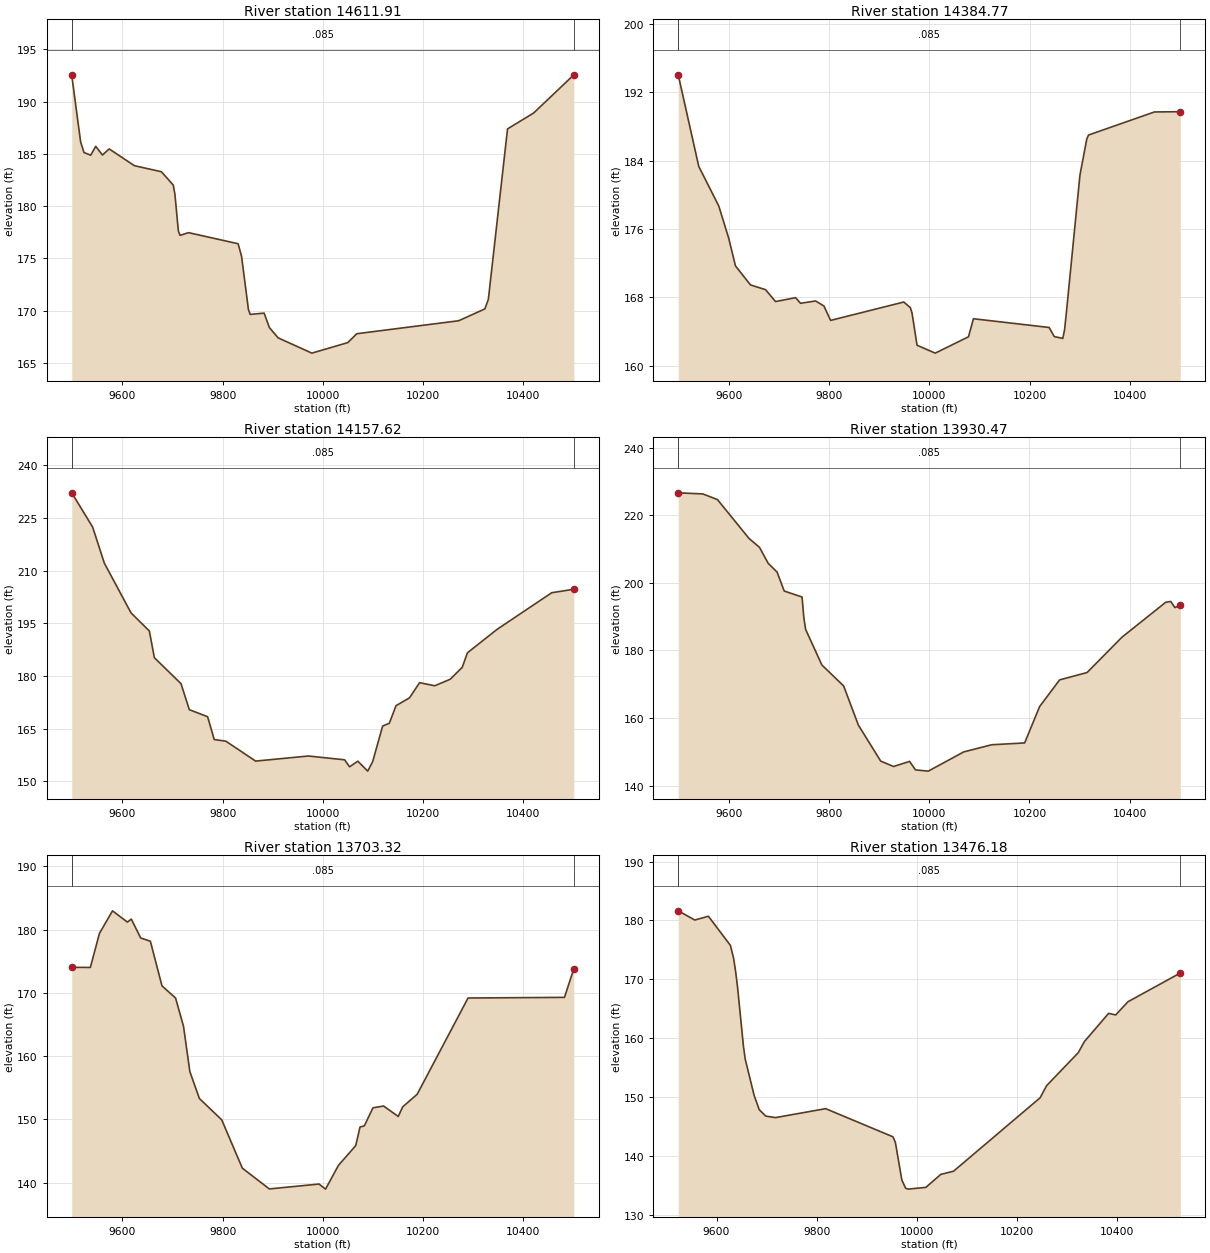
Type RM Length L Ch R = 1 ,14611.91,227.147600,227.147600,227.147600
XS GIS Cut Line= 6
1192535.61431628841946.3115391791192340.10651157841988.801264119
1192186.23343919842032.4948323531192110.67204996842060.426590455
1191898.95813658842149.749344853 1191586.3766377842260.117601717
#Sta/Elev= 30
9499.034192.49729516.763186.1269 9523.46185.12399536.853184.86989546.898185.7189
9560.292184.88389573.685185.46899624.047183.86619677.922 183.2869701.512182.0177
9704.907181.12619711.698177.63699715.093177.20169732.069177.46199830.955176.4002
9837.825175.21469851.564170.11639854.999169.64029882.907169.7648  9893.4168.3835
9910.889167.39789978.202165.938910049.87166.9446 10067.8167.794310271.23169.0362
10323.42170.168810330.38171.081210368.65187.383410420.84188.907410500.98192.5556
#Mann= 3 , 0 , 0
9499.034   0.085       09499.034   0.085       010500.98   0.085       0
#XS Ineff= 2 , 0
       09922.805        10100.52       0
Bank Sta=9499.034,10500.98
Exp/Cntr=0.3,0.1

Type RM Length L Ch R = 1 ,14384.77,227.147500,227.147500,227.147500
XS GIS Cut Line= 6
1192483.11517092841789.7289287631192142.23357619841849.589089572
1191928.86361456841877.5857612881191836.91918964 841894.06153128
1191668.56969331841938.6017649491191504.97753736841994.944113583
#Sta/Elev= 30
9499.008 194.0389539.956183.32569579.929178.69049599.915174.88399613.239171.6855
9643.218169.45789673.198168.90869693.184167.51159733.156167.96919743.149167.3104
9773.129167.58419789.784166.99389803.108165.30969949.138167.45919962.351166.7928
9965.654166.14559975.564 162.40410011.91161.481310078.18163.390310088.18165.5041
10239.24164.4803 10249.4163.419410266.49163.2045 10269.9164.191510273.32166.0522
10300.65182.300910314.32186.532110317.74186.992210449.25189.693810500.96189.7253
#Mann= 3 , 0 , 0
9499.008   0.085       09499.008   0.085       010500.96   0.085       0
#XS Ineff= 2 , 0
       09938.412        10087.23       0
Bank Sta=9499.008,10500.96
Exp/Cntr=0.3,0.1

Type RM Length L Ch R = 1 ,14157.62,227.147600,227.147600,227.147600
XS GIS Cut Line= 6
 1192467.4386214841579.3032017311192156.95287152841629.630736472
1191904.99126141841647.9905829831191817.27149231 841660.38918457
1191676.68996397841698.3300047881191489.93506647841770.827075589
#Sta/Elev= 30
 9499.02232.17389540.681222.41889563.984212.15019617.247 197.9719653.865192.8034
9663.852185.19919717.045177.7866 9733.62170.38069770.086168.37669783.346161.8742
9806.551161.40269865.935155.73049971.206157.178310043.51156.095510053.38154.1036
10069.83155.701310089.64152.870810099.54155.608910119.45165.731410132.75166.5105
10146.05171.516610172.89173.738910193.11 178.06910223.44177.192310254.26 179.061
10278.26182.449410288.55186.582410347.68193.263210456.86203.709410500.95 204.694
#Mann= 3 , 0 , 0
 9499.02   0.085       0 9499.02   0.085       010500.95   0.085       0
#XS Ineff= 2 , 0
       09908.761                       0
Bank Sta=9499.02,10500.95
Exp/Cntr=0.3,0.1

Type RM Length L Ch R = 1 ,13930.47,227.147500,227.147500,227.147500
XS GIS Cut Line= 6
1192386.29597736841218.095214301 1192217.1103752841275.597660815
1192074.04454577841338.6643795881191980.22750604841389.497701372
1191858.79040757841471.7167971061191488.16639109841654.193633329
#Sta/Elev= 30
9499.053226.65259548.204226.32569577.323224.65549640.153 213.1799661.097210.5362
9678.564205.79879696.342203.18749710.564197.5909 9746.12195.81969749.676189.7525
9753.231186.2464 9785.72175.70069829.144169.4998 9858.59157.89489903.075147.2625
9928.725 145.6599960.672147.17259972.497144.65839998.079144.293710068.77149.9778
10124.57152.099910190.31152.632210220.23 163.41110260.11171.295610314.87173.4694
10384.24183.892410471.86194.265410481.97194.497210490.11192.696210500.95193.4068
#Mann= 3 , 0 , 0
9499.053   0.085       09499.053   0.085       010500.95   0.085       0
#XS Ineff= 2 , 0
       0                               0
Bank Sta=9499.053,10500.95
Exp/Cntr=0.3,0.1

Type RM Length L Ch R = 1 ,13703.32,227.147600,227.147600,227.147600
XS GIS Cut Line= 6
1192197.34986976840972.0149997851192075.71622848841035.143439187
1191978.97174659841097.3249687531191873.37049067841176.859350269
1191625.26707099841382.7678024861191380.45479031841547.436240933
#Sta/Elev= 30
9499.034174.03849536.108174.01919554.296179.40989580.359182.9711 9609.99181.1894
9617.833181.66379636.584178.67569655.875178.16749679.025171.11199706.204169.1804
9722.018164.71929734.671157.56089753.706153.29729798.251149.92799839.456142.2798
9893.346139.00049992.409139.772510005.47138.968510031.17142.717110065.66145.8463
10074.28 148.783 10082.9148.975910100.14151.830410121.26152.106110150.59150.4569
 10159.4151.975610188.31153.964710289.84169.185310482.25169.287810500.96173.8109
#Mann= 3 , 0 , 0
9499.034   0.085       09499.034   0.085       010500.96   0.085       0
#XS Ineff= 2 , 0
       0                               0
Bank Sta=9499.034,10500.96
Exp/Cntr=0.3,0.1

Type RM Length L Ch R = 1 ,13476.18,217.303300,217.303300,217.303300
XS GIS Cut Line= 6
 1192019.8319565 840799.891530711191932.42601226840850.078906707
1191808.62704548840937.0057222271191705.76505453 841020.07879501
1191410.77722285841270.915626011 1191226.0822399841408.555050886
#Sta/Elev= 30
9523.632181.63539556.653180.07629583.871180.71329627.745175.76889634.075173.6056
9638.017171.44389641.958168.73429653.784158.6483 9657.34156.46869675.097150.3261
9685.318 147.8969698.454146.8135  9717.6146.55589817.853148.07429952.131143.2996
9956.971142.35059969.915135.96139977.389134.57359982.441134.4244 10017.8134.7242
10047.68 136.92810073.08137.466510245.93149.929510258.72 151.97210321.93157.5714
10334.38159.472110382.51164.244510396.61163.974610421.27166.221210525.58171.0825
#Mann= 3 , 0 , 0
9523.632   0.085       09523.632   0.085       010525.58   0.085       0
#XS Ineff= 2 , 0
       0                10142.11       0
Bank Sta=9523.632,10525.58
Exp/Cntr=0.3,0.1

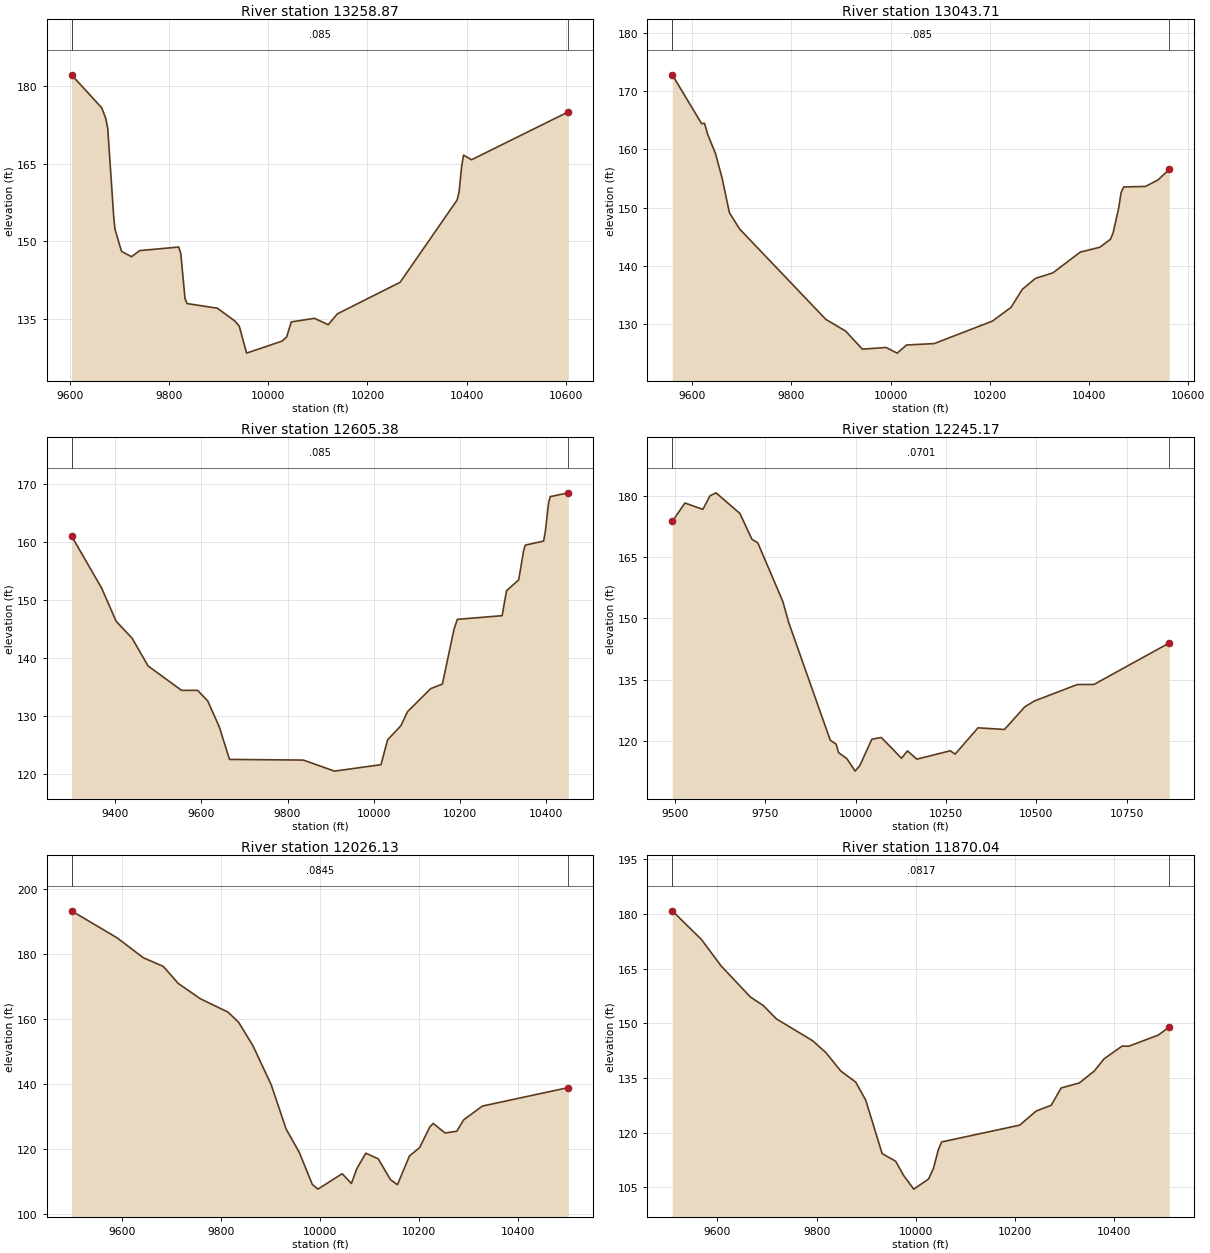
Type RM Length L Ch R = 1 ,13258.87,215.167700,215.167700,215.167700
XS GIS Cut Line= 6
1191799.88003908840677.9244507441191714.37472085840731.271705671
1191594.65892102 840823.724030241191496.49262134840912.287997823
1191255.39027276841146.8956221231191038.44764158841325.579079541
#Sta/Elev= 30
9603.358182.25199664.253 175.8669672.552173.76719676.495171.78529688.323 154.944
9690.977152.3412 9704.17148.05279724.399 147.0139740.646148.19729819.559148.8862
 9823.78147.57719832.223138.89979836.444137.9305 9897.55137.03569932.764134.5482
 9941.63133.55619956.323128.3324 10027.8130.661110037.13 131.46110046.47 134.376
10093.13 135.077   10121133.832610139.55135.955410265.93142.056710380.81157.9871
10384.84159.598810389.86164.433310393.81166.690910409.95 165.79710605.27175.0877
#Mann= 3 , 0 , 0
9603.358   0.085       09603.358   0.085       010605.27   0.085       0
#XS Ineff= 2 , 0
       0                10086.04       0
Bank Sta=9603.358,10605.27
Exp/Cntr=0.3,0.1

Type RM Length L Ch R = 1 ,13043.71,438.329400,438.329400,438.329400
XS GIS Cut Line= 6
1191677.03156995840496.8502671111191591.52625171840550.197522037
1191471.81045189840642.6498466061191373.64415221840731.213814189
1191132.54180363 840965.821438491190915.59917245841144.504895907
#Sta/Elev= 30
9559.701172.86989618.731164.47289624.789164.50599631.086162.60729646.857159.2995
9660.285155.02159674.876149.11259695.185146.32149869.469130.70259909.237128.6981
9942.991125.58239990.748125.871810013.04124.897910032.27 126.30210087.83126.5422
10205.22 130.421 10242.8132.793710265.32135.8795 10291.9137.778110327.08138.7324
10382.33142.313910421.89143.150810443.22144.524210448.56 145.62210459.76149.8912
10464.57152.547710469.91153.548210513.83 153.63110538.79154.736210561.61 156.554
#Mann= 3 , 0 , 0
9559.701   0.085       09559.701   0.085       010561.61   0.085       0
#XS Ineff= 2 , 0
       0                10085.75       0
Bank Sta=9559.701,10561.61
Exp/Cntr=0.3,0.1

Type RM Length L Ch R = 1 ,12605.38,360.203000,360.203000,360.203000
XS GIS Cut Line= 6
1191716.87130699840240.0362592791191357.87419158840326.394177392
1191269.90757143840346.5031032561191203.11782545840358.139293298
1191135.79183602840387.5071855931190664.76529515840678.046921074
#Sta/Elev= 30
9298.207160.98459368.198151.99659401.942146.2886 9439.06143.36559476.179138.5865
9553.791134.39959590.909134.3941 9614.53132.59269641.526128.09459665.147122.5107
9836.748122.3937 9909.06120.493210016.99121.600710032.41125.888610063.25128.3044
10078.67130.729410132.64134.699110159.62135.4758 10186.6144.905610194.31146.6171
10298.39147.253610308.57151.541710336.94153.4208 10348.5158.537910352.32159.3965
10394.76160.095610398.61161.665110406.32166.663810410.18167.746410452.35168.3987
#Mann= 3 , 0 , 0
9298.207   0.085       09298.207   0.085       010452.35   0.085       0
#XS Ineff= 2 , 0
       09808.965                       0
Bank Sta=9298.207,10452.35
Exp/Cntr=0.3,0.1

Type RM Length L Ch R = 1 ,12245.17,219.047100,219.047100,219.047100
XS GIS Cut Line= 6
1191571.97832714840082.8554786211191243.22711112840120.559755406
1190960.12477686840107.0028018721190889.29791568840108.649536363
1190674.85826175840142.1696281351190205.36853297 840198.90513008
#Sta/Elev= 30
9492.046173.74379527.046178.26759576.679176.71019596.532180.03519613.076180.7615
9679.286175.7052 9712.34169.41189728.836168.48069797.949154.15819814.404148.9475
 9929.29120.14289945.723119.14819952.296117.08659975.302 115.6139998.313112.5493
10011.47113.954410044.37120.366610070.68120.800210126.56115.714110142.97117.5047
10169.22115.483710261.69117.539710274.97116.709610338.28123.163510411.57122.7615
10467.75128.300510494.19 129.72810613.16133.770810659.43133.797210867.51143.9532
#Mann= 3 , 0 , 0
9492.046  0.0701       09492.046  0.0701       010867.51  0.0701       0
#XS Ineff= 2 , 0
       0                10253.67       0
Bank Sta=9492.046,10867.51
Exp/Cntr=0.3,0.1

Type RM Length L Ch R = 1 ,12026.13,156.088400,156.088400,156.088400
XS GIS Cut Line= 6
 1191442.1022358 839788.95869829 1191305.3840102839792.361545987
1191193.43457878839818.2859106251191093.00611648839857.657266442
1190834.38460602839990.4403864711190494.20132686840074.814536473
#Sta/Elev= 30
9499.061193.15539591.043184.85619643.926178.73759684.024176.09769714.387 170.842
9758.841166.1593 9814.67162.0466 9836.15158.90979864.952151.71159901.778139.7199
9931.729126.16579958.168119.03049984.608109.13649995.939107.695110044.82112.4297
10063.47 109.41910074.36114.003610092.52118.731210117.56116.990610142.27110.5769
10156.26109.053810180.41117.873610201.12120.477810221.66126.833810228.46127.8714
10252.23124.9312   10276125.479410289.59128.957710327.57133.204610500.95138.8822
#Mann= 3 , 0 , 0
9499.061  0.0845       09499.061  0.0845       010500.95  0.0845       0
#XS Ineff= 2 , 0
       0                               0
Bank Sta=9499.061,10500.95
Exp/Cntr=0.3,0.1

Type RM Length L Ch R = 1 ,11870.04,241.039500,241.039500,241.039500
XS GIS Cut Line= 6
1191401.26312525 839746.756235941191301.95381457 839730.12493153
1191232.71630949839728.8342226881191175.65660984839733.413804733
1190620.39410776839837.1733710461190413.14326308839868.065393221
#Sta/Elev= 30
9508.911 180.8919567.662173.03519607.307165.78319666.386157.24989692.679154.8649
 9719.01151.22689791.906145.24189818.587141.98789848.712136.92959878.838133.8822
9898.922128.9512 9932.04114.26849959.174112.1913 9975.87108.1748 9995.75104.5215
10025.58107.291910035.53110.246310045.48115.420310052.12117.473610209.33122.0785
10242.78125.970710272.89127.525110292.96132.281610329.59133.652310359.51136.8983
10379.46140.272810415.99143.787110429.23143.729610488.81146.793610510.77148.9993
#Mann= 3 , 0 , 0
9508.911  0.0817       09508.911  0.0817       010510.77  0.0817       0
#XS Ineff= 2 , 0
       0                               0
Bank Sta=9508.911,10510.77
Exp/Cntr=0.3,0.1

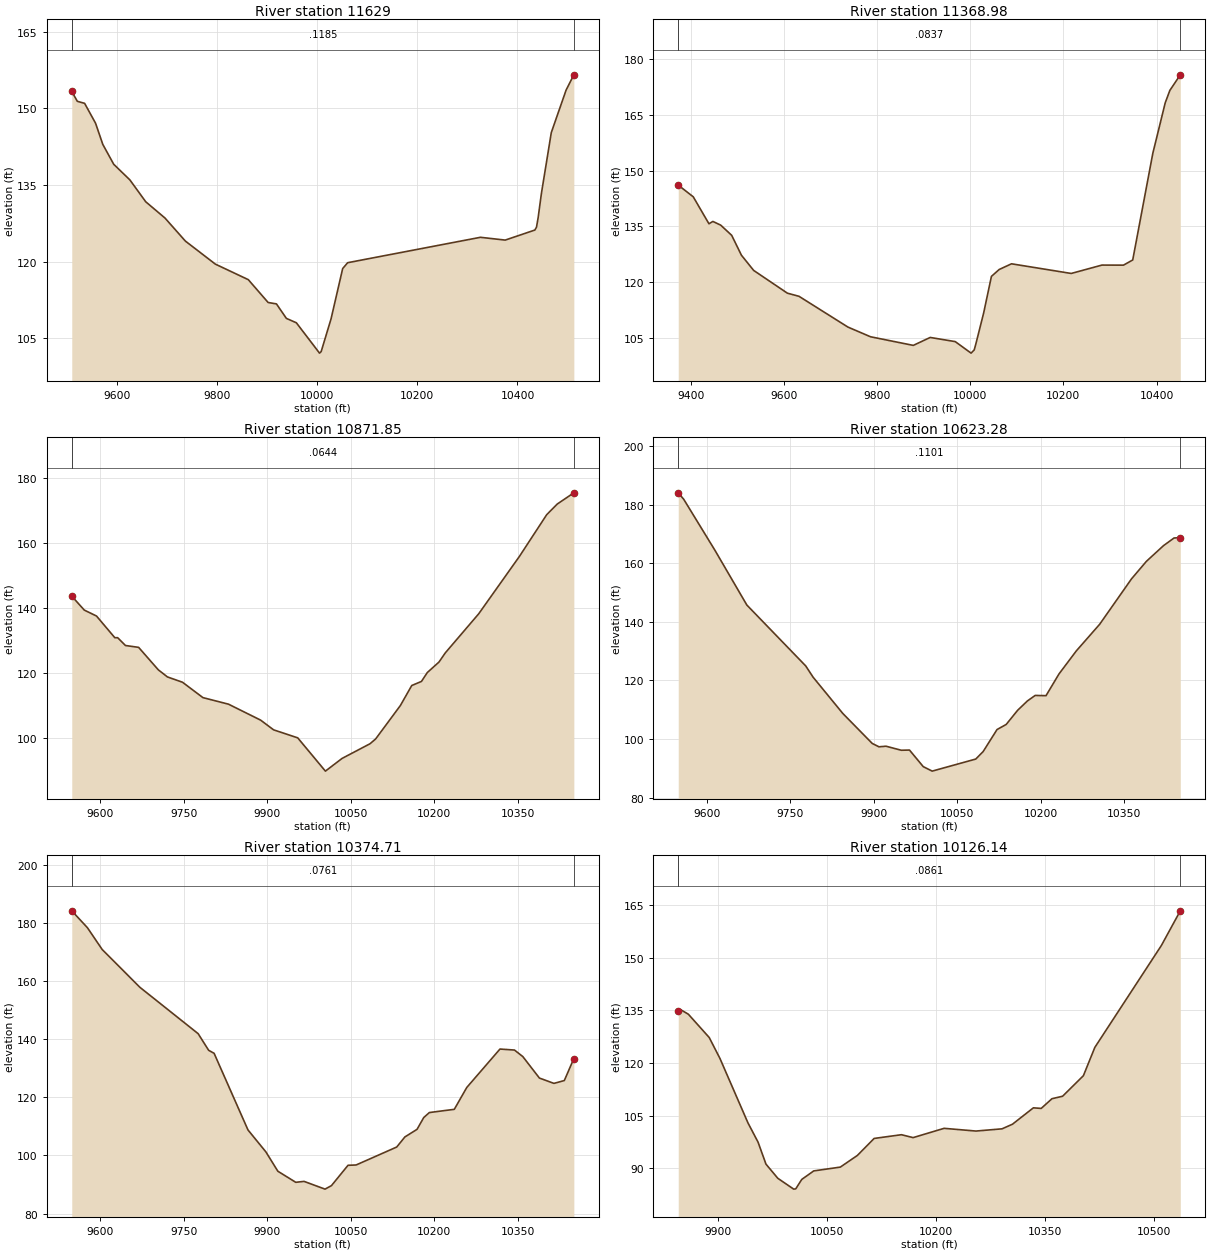
Type RM Length L Ch R = 1 ,   11629,260.013400,260.013400,260.013400
XS GIS Cut Line= 6
1191337.35492311839623.3477728631191181.70695634839555.034738679
1191102.35047104839534.571946302 1191040.9748105839529.533726769
1190583.73136733839587.3759886481190357.12133166839599.175774689
#Sta/Elev= 30
9510.606153.33079521.726 151.3969536.241151.00289558.013  147.129572.527142.9612
9594.299139.06279626.505136.00839658.214131.71279696.582128.52849737.255124.0142
9797.147 119.4929862.861116.4505 9902.44111.97489918.998111.70139938.868108.8585
9958.738 108.00210004.99102.052710008.28102.356610028.06 108.792 10051.2118.6299
10061.17119.771910326.14124.750910375.49124.203310434.64126.170510437.92126.7276
10441.21128.582910447.77133.367810467.46145.2667   10497153.597810512.46156.5896
#Mann= 3 , 0 , 0
9510.606  0.1185       09510.606  0.1185       010512.46  0.1185       0
#XS Ineff= 2 , 0
       0                               0
Bank Sta=9510.606,10512.46
Exp/Cntr=0.3,0.1

Type RM Length L Ch R = 1 ,11368.98,497.137900,497.137900,497.137900
XS GIS Cut Line= 6
1191329.48499301839575.3165614311191132.66648105839417.263135195
1190995.87761819839319.0512215791190926.45255759839285.111130252
1190644.47392562839322.2375565471190353.72749498839290.951937199
#Sta/Elev= 30
9373.487146.10799405.743142.95489439.405135.70819447.821136.34019464.652135.3448
9488.209132.60219509.168127.24839535.367123.17169607.716117.05669632.679116.2121
 9737.69 107.9389786.157105.33659877.918103.01939914.195105.15289967.935104.0351
10001.91100.938310008.67101.803210012.06103.339610028.86111.6942 10045.6121.5694
10062.25 123.41910088.69124.949910216.84122.355110282.71124.605610328.97124.5897
10348.83125.980210391.93154.640710418.53168.213110428.51171.567410450.94175.7511
#Mann= 3 , 0 , 0
9373.487  0.0837       09373.487  0.0837       010450.94  0.0837       0
#XS Ineff= 2 , 0
       0                               0
Bank Sta=9373.487,10450.94
Exp/Cntr=0.3,0.1

Type RM Length L Ch R = 1 ,10871.85,248.568900,248.568900,248.568900
XS GIS Cut Line= 6
1191347.36242054839520.8497157661191261.81250834839436.743345168
1191196.02916459839330.9322976241191115.12564635838975.493945304
1191064.33539956 838850.250195361190989.50276294838713.244554668
#Sta/Elev= 30
 9549.12143.69759571.622139.41769593.618137.58419626.464130.92569631.469130.9425
9645.537128.5348 9669.19127.96419704.566 121.0629720.912118.88159748.063117.2376
9784.728112.5167 9830.61110.50319888.301105.60339911.675102.61229954.969 100.156
10004.6989.9269510034.6193.8286210084.8598.3442610094.9599.8197610139.26110.0623
10159.79116.235210177.24117.499410187.72120.222310208.67123.442910220.06126.2689
10280.05138.276910353.29155.943210402.21168.740910421.14 172.00910450.93175.4544
#Mann= 3 , 0 , 0
 9549.12  0.0644       0 9549.12  0.0644       010450.93  0.0644       0
#XS Ineff= 2 , 0
       0                               0
Bank Sta=9549.12,10450.93
Exp/Cntr=0.3,0.1

Type RM Length L Ch R = 1 ,10623.28,248.568900,248.568900,248.568900
XS GIS Cut Line= 6
1191595.21968712 839424.060619171191537.91560593839285.395411589
1191483.95766193839185.3874674251191362.80008914839021.724475863
1191268.00917895838908.2454917681191119.08265202838663.740773958
#Sta/Elev= 30
9549.069 184.0079558.898181.81679615.238164.31839672.298145.71179778.109124.9147
9791.333121.08199844.664108.70479897.56598.460639909.62497.315489922.28597.51969
9949.71996.145089964.49196.204999989.16790.55414 10005.2  89.01610083.4893.13488
10096.7195.67487 10121.7103.205410138.16104.948410158.78 109.79210176.33112.9746
10190.22114.8482 10209.7114.772510233.08122.201110264.15 130.05510306.12139.1509
10363.36154.658210390.06160.627110420.59165.949210439.66168.587510450.94168.7064
#Mann= 3 , 0 , 0
9549.069  0.1101       09549.069  0.1101       010450.94  0.1101       0
#XS Ineff= 2 , 0
       0                               0
Bank Sta=9549.069,10450.94
Exp/Cntr=0.3,0.1

Type RM Length L Ch R = 1 ,10374.71,248.568900,248.568900,248.568900
XS GIS Cut Line= 6
1191707.42341241839308.1247564731191691.34114198839222.551995386
1191673.78433187839162.0813312811191575.32639644838926.591931647
1191539.56917272838864.5551259131191343.55275151838487.770352945
#Sta/Elev= 30
9549.058184.10579577.163178.30699603.802170.78199671.595157.78629776.114141.8622
9794.944136.1463 9804.74135.11799865.568108.77269897.771101.2142 9919.2494.57291
9951.44390.758719966.305 91.0771   1000488.4146910015.5689.61888 10045.396.60452
10059.8996.7202610132.82102.891710147.41106.352610169.29108.971910181.32113.0242
10191.49114.748810236.23 115.849 10258.6123.360510318.26136.578310344.36 136.232
10359.27133.9927 10389.1126.6086 10415.2124.773910433.84125.751410450.96133.3022
#Mann= 3 , 0 , 0
9549.058  0.0761       09549.058  0.0761       010450.96  0.0761       0
#XS Ineff= 2 , 0
       0                10116.98       0
Bank Sta=9549.058,10450.96
Exp/Cntr=0.3,0.1

Type RM Length L Ch R = 1 ,10126.14,334.991900,334.991900,334.991900
XS GIS Cut Line= 6
1191851.20484698838913.0066564081191812.36249724 838833.25446476
1191736.77218452838733.4286404551191694.93965408838665.721989408
1191606.82251674838480.4044534421191518.77603278838309.707865238
#Sta/Elev= 30
9844.804134.78379848.341135.20119858.725133.93269887.449127.28769902.274121.2855
9940.813102.90859954.68897.420259965.56491.14818 9981.88 87.106410003.7484.01387
10006.58 84.096410014.8386.7787610031.31 89.210110067.9490.3016910091.4593.63734
10114.4898.4790210152.0199.5424310168.1398.7166410210.81101.3642 10254.6100.5861
10290.54 101.22210304.91102.542310333.66107.214310344.46107.049510359.23109.8155
 10373.9110.523610402.53116.390710418.29124.472610509.88153.551310535.92163.4365
#Mann= 3 , 0 , 0
9844.804  0.0861       09844.804  0.0861       010535.92  0.0861       0
#XS Ineff= 2 , 0
       0                10111.19       0
Bank Sta=9844.804,10535.92
Exp/Cntr=0.3,0.1