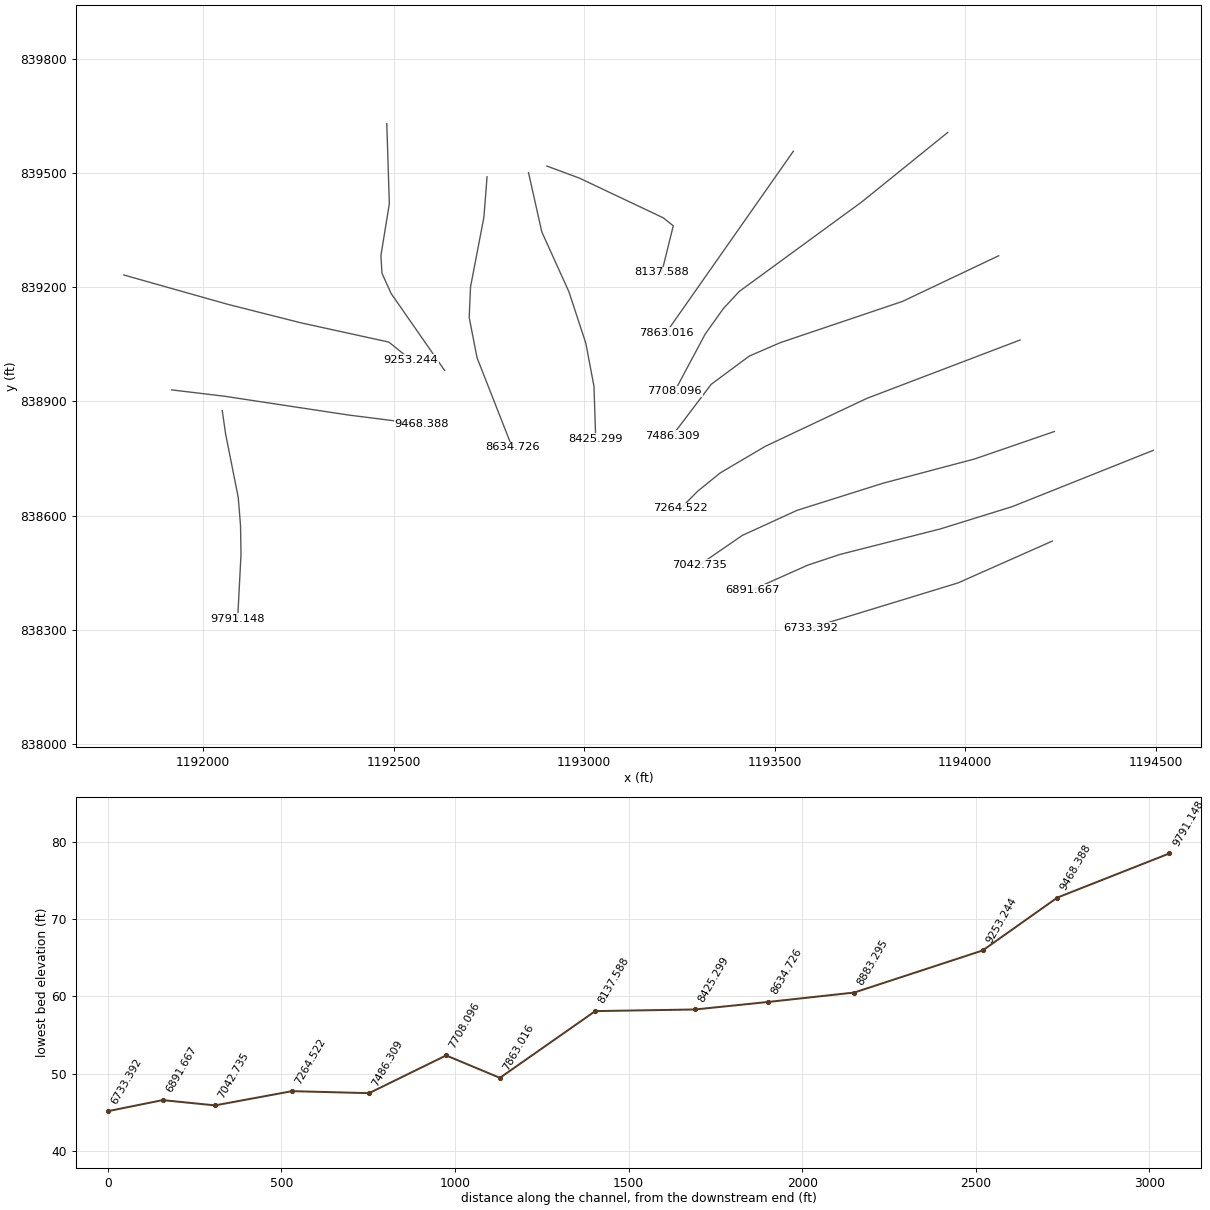
HEC-RAS study 109_ras.prj: 109

--- 109_ras.g01 (geometry) --- (continued)

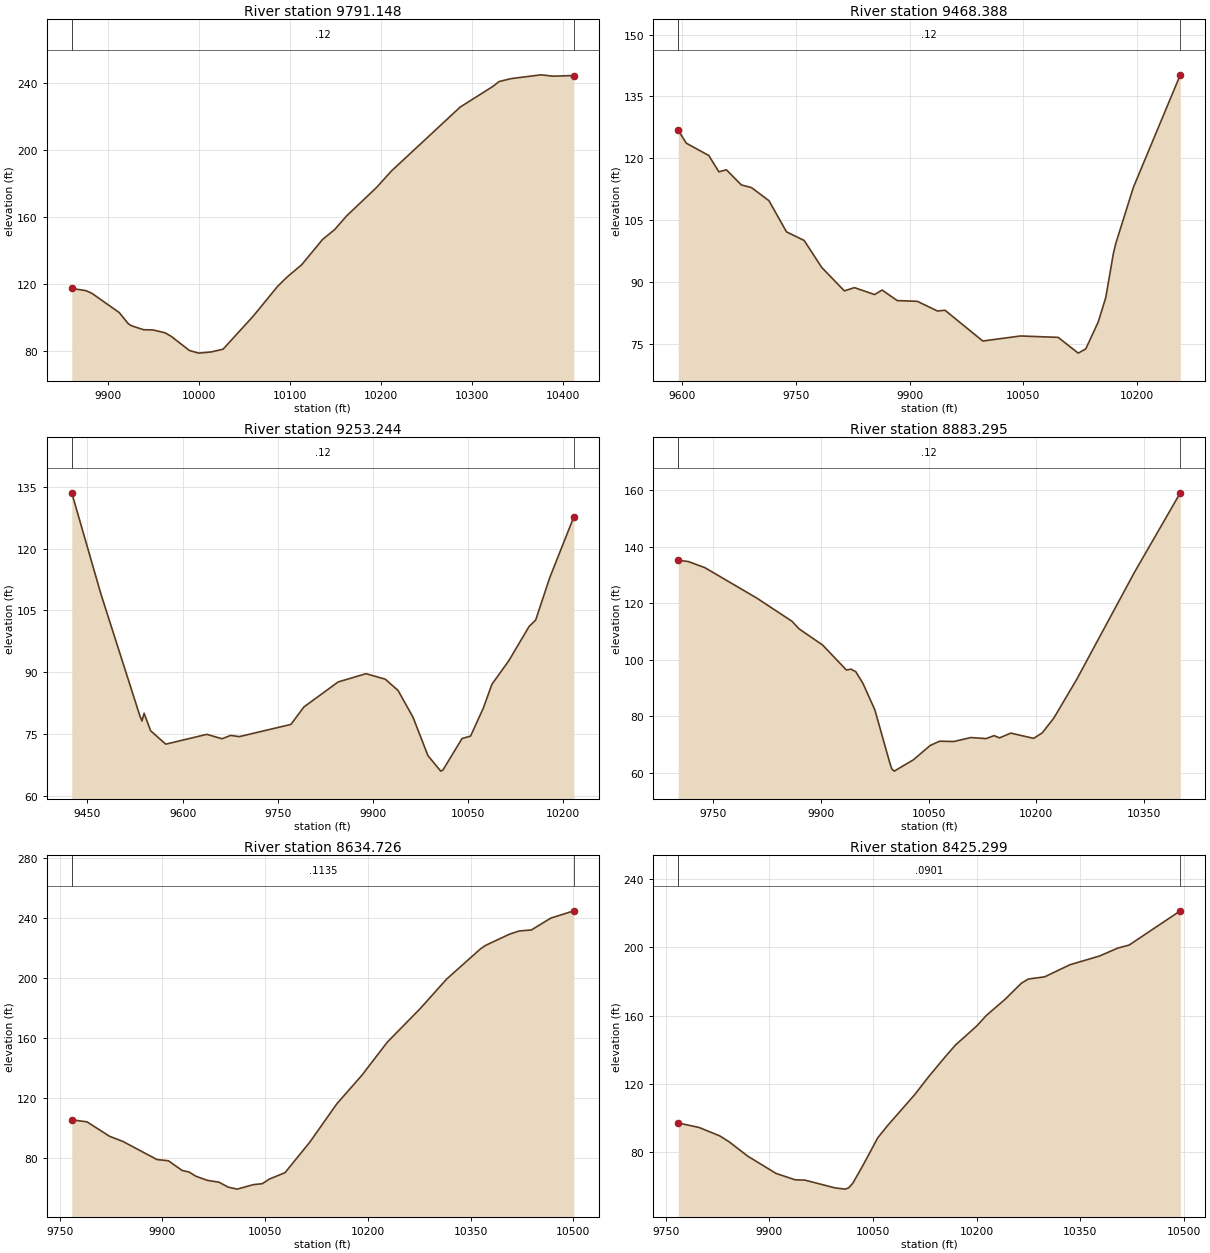
Type RM Length L Ch R = 1 ,9791.148,322.759800,322.759800,322.759800
XS GIS Cut Line= 6
1192050.08459715838875.9841040721192058.96429918838813.992458259
1192092.00681264838648.4369158211192098.02566019838574.404342636
1192099.29744373838498.5566959061192090.46847078838329.025656947
#Sta/Elev= 30
 9860.65117.19429876.351 115.893 9882.98114.22719912.809102.77089922.75296.07402
9926.10294.903619939.53392.505259949.60692.391699963.03790.676839969.75288.58451
9989.89880.062689999.97178.48441 10013.479.1609910026.83 80.834210060.18 100.776
10086.77118.503810096.69123.834710113.15131.410610136.19146.606110149.36152.4536
10162.53160.663310195.35 177.67310211.76187.572810287.24225.831910323.35238.2775
10329.92241.095210343.08242.877510375.97245.148210389.13 244.33610412.08244.7134
#Mann= 3 , 0 , 0
 9860.65    0.12       0 9860.65    0.12       010412.08    0.12       0
#XS Ineff= 2 , 0
       09885.823                       0
Bank Sta=9860.65,10412.08
Exp/Cntr=0.3,0.1

Type RM Length L Ch R = 1 ,9468.388,215.144100,215.144100,215.144100
XS GIS Cut Line= 4
1191917.16763976838930.4063910391192055.32061961838913.809539825
1192381.59100476838864.3746329691192573.08310315 838840.16298835
#Sta/Elev= 30
9594.787126.81089605.388123.66969635.128120.67679648.346116.72679658.259117.2187
9678.085113.54169691.303112.91399714.434109.7316 9737.58102.17259760.808100.0978
9784.03693.547699813.90187.867279827.17488.65346 9853.7286.982179863.67588.06849
9883.584 85.51449910.13185.333219936.67782.984759946.63283.171219996.40675.71354
10046.1876.9353810095.84 76.5988 10122.372.7769210132.2273.7926910148.7680.35394
10158.68 86.2856 10168.696.88078 10171.999.4012610195.05112.961910256.94140.2378
#Mann= 3 , 0 , 0
9594.787    0.12       09594.787    0.12       010256.94    0.12       0
#XS Ineff= 2 , 0
       09933.386                       0
Bank Sta=9594.787,10256.94
Exp/Cntr=0.3,0.1

Type RM Length L Ch R = 1 ,9253.244,369.948800,369.948800,369.948800
XS GIS Cut Line= 5
1191791.70729941839231.9514195021192064.63856608839154.914368451
1192256.13066447839106.4910791961192487.24181765839055.866731346
1192544.46934134839009.644500703
#Sta/Elev= 30
9425.264133.5987 9471.11109.05229532.47379.440579535.88278.139179539.29180.01141
9549.51875.760739573.381 72.49769638.15274.883019662.01573.813759675.65174.62292
9689.28774.328529770.64977.297789790.95481.522259845.09987.625729889.09389.63174
 9919.4588.289669939.60285.533059963.11379.029829986.62369.7053510006.7765.94304
10010.1366.1845410040.3673.87501 10053.874.4596610073.9581.2936110087.3887.04793
10114.2592.8303810145.92101.092110156.37102.6714 10178.6112.994510216.53127.7625
#Mann= 3 , 0 , 0
9425.264    0.12       09425.264    0.12       010216.53    0.12       0
#XS Ineff= 2 , 0
       09893.683                       0
Bank Sta=9425.264,10216.53
Exp/Cntr=0.3,0.1

Type RM Length L Ch R = 1 ,8883.295,248.568900,248.568900,248.568900
XS GIS Cut Line= 6
1192481.90226669839629.0883129931192488.56230111839418.850797899
1192466.43701229839282.6621728251192469.26127166839236.425207194
1192493.17511213839183.4867255681192633.62627289 838981.42162876
#Sta/Elev= 30
9701.297135.15129715.392134.69199738.423132.52939810.708121.77079859.947113.5309
9869.794110.84089902.619105.11579935.53396.317189942.123 96.59099948.71395.68315
9958.65891.573449975.28182.17714 9995.4463.988899998.824  61.29610002.2460.50427
10029.1164.5434910052.2969.5788510065.4171.0958910085.2270.9920410109.0772.39445
10130.1872.0193410141.4673.0770610148.9972.2743210164.61 73.965610196.57 72.1025
10208.5674.0679110224.5479.2733610256.1792.8352310336.64130.744910400.84159.0249
#Mann= 3 , 0 , 0
9701.297    0.12       09701.297    0.12       010400.84    0.12       0
#XS Ineff= 2 , 0
       0                               0
Bank Sta=9701.297,10400.84
Exp/Cntr=0.3,0.1

Type RM Length L Ch R = 1 ,8634.726,209.426700,209.426700,209.426700
XS GIS Cut Line= 6
 1192744.9980854839489.648078542 1192736.7938181839383.930677033
1192701.66355361839200.6521936191192698.13142095839120.292596143
1192718.78597624839014.6097817961192810.89412513838779.965522274
#Sta/Elev= 30
9767.588105.4634 9789.87 104.093 9822.7394.50211 9842.52 91.00149892.10378.97689
9908.69178.186929928.77871.716419938.84170.708659948.90467.856229965.67565.12247
9982.447 63.92179995.864 60.638710009.2459.2844610032.61 62.255510045.9662.92409
10055.9765.9404510079.08 70.264210115.2890.5978310154.75116.156710191.21135.0703
10228.42157.209210276.54179.576910314.93199.158310364.56219.355710371.64 221.592
10407.02229.165310421.17231.280610438.86231.937510467.16239.829210500.87 244.693
#Mann= 3 , 0 , 0
9767.588  0.1135       09767.588  0.1135       010500.87  0.1135       0
#XS Ineff= 2 , 0
       0                               0
Bank Sta=9767.588,10500.87
Exp/Cntr=0.3,0.1

Type RM Length L Ch R = 1 ,8425.299,287.711100,287.711100,287.711100
XS GIS Cut Line= 6
 1192853.8356895839500.5318389431192888.70122042839345.033441403
1192959.80293401  839188.14765541193004.28332326839052.605911232
1193025.62115066838939.6553209671193030.14991899838802.772210003
#Sta/Elev= 30
9768.03297.099639798.23694.459089828.14589.519319841.59686.092299868.49877.68269
9909.49967.542529937.23463.783919951.37663.603589994.95559.0385210009.6658.31695
10014.7359.0522710020.6861.7451510035.4572.2555110056.7988.3560410071.0795.56056
10110.08113.569510130.99124.458110155.38136.287210169.32142.742310200.29153.9945
10213.96 160.08910241.28169.615610264.86179.039310274.95181.476310298.46 182.737
10334.99189.828810377.97194.960510404.28199.592310420.73 201.37510494.84221.4387
#Mann= 3 , 0 , 0
9768.032  0.0901       09768.032  0.0901       010494.84  0.0901       0
#XS Ineff= 2 , 0
       0                               0
Bank Sta=9768.032,10494.84
Exp/Cntr=0.3,0.1

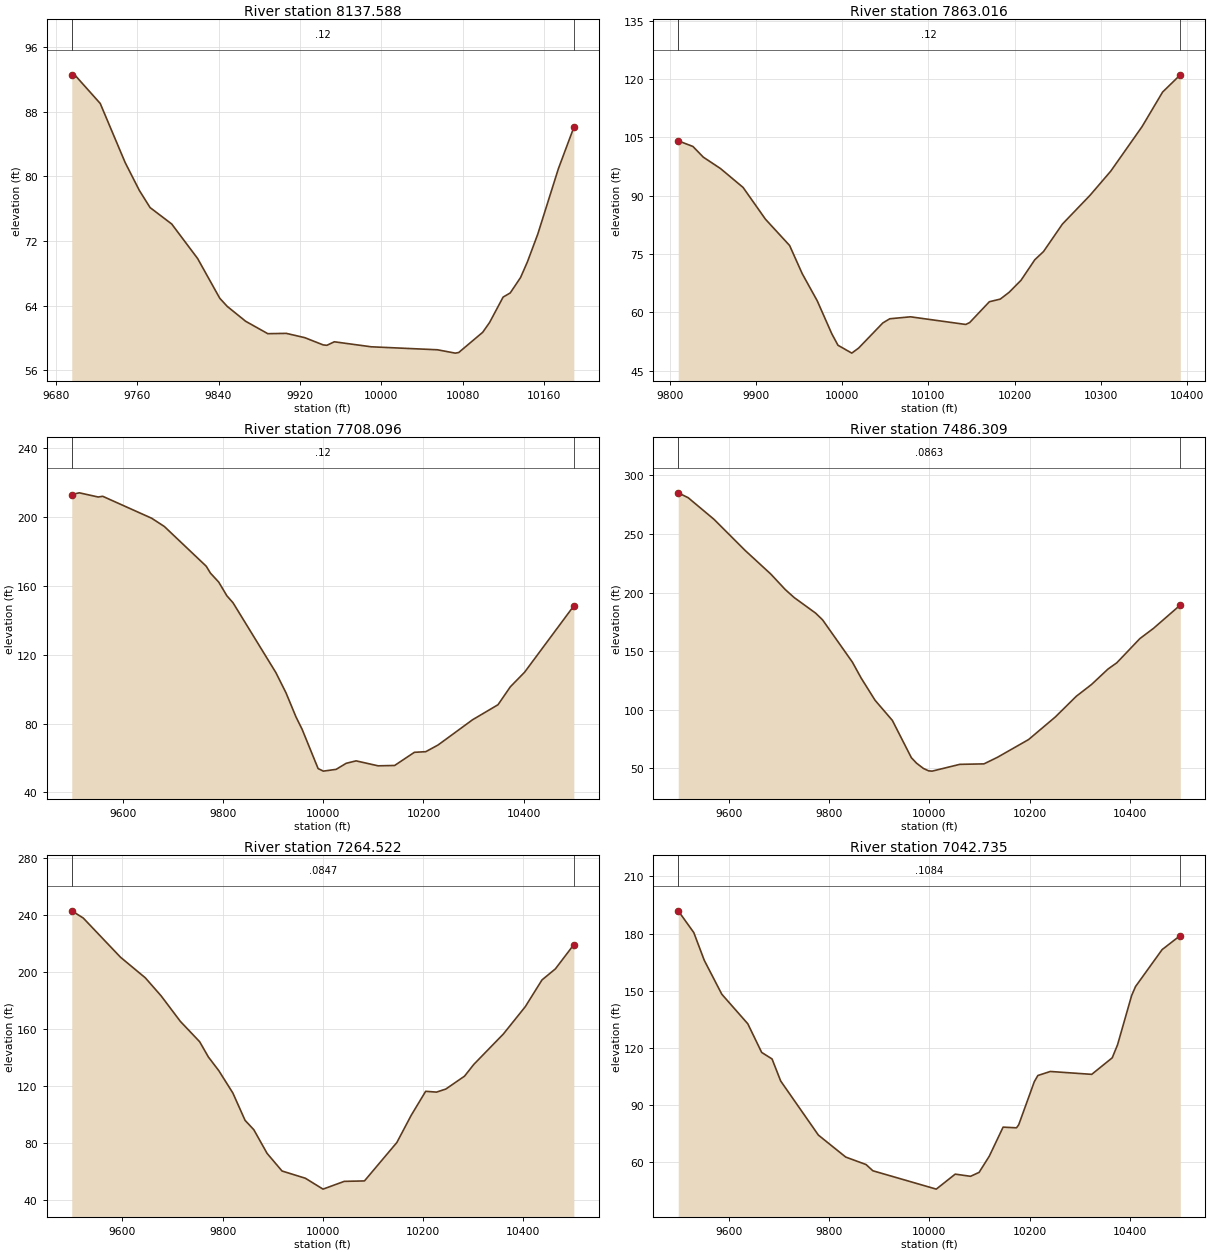
Type RM Length L Ch R = 1 ,8137.588,274.572700,274.572700,274.572700
XS GIS Cut Line= 5
1192902.13209069839517.8089671741192986.64440411839486.489698082
1193207.58168095839381.9040049021193233.72810423839360.986866266
1193203.65971747839239.405997977
#Sta/Elev= 30
9695.78192.554439699.24692.468199723.73889.01167 9748.2381.699269762.22678.23452
9772.72276.124219794.008 74.08579819.41769.821679841.19664.898399848.45563.89891
9866.60562.051479888.38460.512749906.53360.552189924.68260.022589942.83259.12227
9946.46259.075179953.72159.51001 9990.0258.8898610055.0958.5209110072.5158.10643
10075.8958.1758310099.5560.6876610106.3161.9031710119.5965.0440810126.5865.55647
10136.7267.4638810143.48 69.406510153.6272.82885 10173.9 80.937110189.0886.05268
#Mann= 3 , 0 , 0
9695.781    0.12       09695.781    0.12       010189.08    0.12       0
#XS Ineff= 2 , 0
       0                               0
Bank Sta=9695.781,10189.08
Exp/Cntr=0.3,0.1

Type RM Length L Ch R = 1 ,7863.016,154.919500,154.919500,154.919500
XS GIS Cut Line= 2
1193548.99811947839556.806836665 1193214.5358057839079.817968726
#Sta/Elev= 30
9809.718104.10249826.758102.65569838.77999.909849858.81496.961229885.00692.10195
9910.90583.941459938.95577.171949953.581 69.92429971.01162.937569987.86854.47102
9995.05351.5098110011.0849.4800110019.0950.7933110047.14 57.255110055.1658.32125
 10079.258.8224410143.3156.8569410147.8857.3462710170.7362.7034110183.3863.38079
10193.59 65.119210207.4268.2144710223.4573.5070210233.5975.6238310255.5182.69264
10287.5790.0974810311.6196.3159510347.88107.753610371.71116.645710392.28121.0862
#Mann= 3 , 0 , 0
9809.718    0.12       09809.718    0.12       010392.28    0.12       0
#XS Ineff= 2 , 0
       0 9913.79                       0
Bank Sta=9809.718,10392.28
Exp/Cntr=0.3,0.1

Type RM Length L Ch R = 1 ,7708.096,221.787000,221.787000,221.787000
XS GIS Cut Line= 6
1193953.76234389839605.8320550931193728.90421855839424.067136363
1193406.93590833839188.7873340591193365.04219876839143.623361992
1193317.50907449839076.8158629281193237.45788162838926.830467907
#Sta/Elev= 30
9498.162213.06649513.228214.06359550.831211.64149559.949212.04369657.639199.2962
9682.914194.50489766.467171.43129774.822167.43589791.431162.19559807.739154.2273
 9819.97150.1782 9905.54 109.5819925.58397.925949945.62683.844149957.65276.79451
9989.72153.8733310000.1452.3794210025.7453.4098110045.66 56.912910065.5758.34118
10109.3955.4625710142.4555.6683210181.7963.3057210204.58 63.675610229.1467.56783
10297.8882.2136610348.7390.9558410373.25101.350810401.74109.838310500.04148.4126
#Mann= 3 , 0 , 0
9498.162    0.12       09498.162    0.12       010500.04    0.12       0
#XS Ineff= 2 , 0
       0                               0
Bank Sta=9498.162,10500.04
Exp/Cntr=0.3,0.1

Type RM Length L Ch R = 1 ,7486.309,221.787100,221.787100,221.787100
XS GIS Cut Line= 6
1194087.74153068839282.4013731581193835.13385127839162.521093136
1193515.07528757839054.5382476521193433.26357285839019.188092202
1193333.17509961838944.9162850041193230.69048496838809.690342531
#Sta/Elev= 30
9499.042285.13859518.861280.97399570.396262.51739632.974235.77369683.591215.8347
9712.481202.60169730.329195.7332 9773.04 182.4639787.126176.64969846.564140.5691
9864.045126.97279891.828107.99469926.31790.804269964.25558.960899974.60254.26797
9988.39849.776399998.74447.7408610005.6847.5031510060.8653.2869110109.1553.69876
10135.9459.2859710198.1274.4543410251.5393.7578610293.34111.418210323.82 121.511
10356.57134.650810374.22140.021310420.22160.672310447.23169.351710500.91189.3388
#Mann= 3 , 0 , 0
9499.042  0.0863       09499.042  0.0863       010500.91  0.0863       0
#XS Ineff= 2 , 0
       0                               0
Bank Sta=9499.042,10500.91
Exp/Cntr=0.3,0.1

Type RM Length L Ch R = 1 ,7264.522,221.787000,221.787000,221.787000
XS GIS Cut Line= 6
1194143.88506885839061.2839881121193741.87911581838908.165787185
1193474.68484514838781.9653850391193357.06774777838712.570696183
1193298.25787974838664.8854562011193253.43058096 838619.84024774
#Sta/Elev= 30
9499.036243.05529522.013237.97379596.287 210.4979645.802196.04229677.417183.3494
 9715.79165.44299754.164151.23929771.606140.52119792.537130.83089820.445115.2523
9844.86596.020679862.31489.45422 9888.7772.845759918.59860.482829965.17555.39685
10000.39  47.76310042.7453.2070510083.1153.5220410147.7780.5035510176.5199.65414
10205.25116.411910226.87115.8412 10245.5118.003210282.74127.025910301.49135.3605
10360.34156.645910404.03175.801310437.36194.5775 10464.1202.323110500.91219.3603
#Mann= 3 , 0 , 0
9499.036  0.0847       09499.036  0.0847       010500.91  0.0847       0
#XS Ineff= 2 , 0
       0                               0
Bank Sta=9499.036,10500.91
Exp/Cntr=0.3,0.1

Type RM Length L Ch R = 1 ,7042.735,151.067900,151.067900,151.067900
XS GIS Cut Line= 6
1194233.74298013838821.1037643861194024.20779157838748.985658189
1193784.60198427838685.5569014211193558.50150814838614.220383964
1193414.95428396838548.4941529691193302.12441554838470.915611515
#Sta/Elev= 30
9499.049191.96889530.077 180.5699551.028165.98439585.947148.22479637.924132.6741
9665.531117.66699686.237114.24389703.491 102.6629778.73474.274599833.31162.74445
9873.89558.818229887.41555.5576810013.9345.9244110051.7353.7903310082.3652.65485
10099.3754.7095610119.7963.2379310147.3178.4535510173.9578.0979910178.4179.67258
 10209.6102.336110216.67 105.54710241.44107.665710324.17106.156110365.07114.8461
10375.66121.659910403.83147.559410411.58152.248210464.61171.622610500.91179.0172
#Mann= 3 , 0 , 0
9499.049  0.1084       09499.049  0.1084       010500.91  0.1084       0
#XS Ineff= 2 , 0
       0                               0
Bank Sta=9499.049,10500.91
Exp/Cntr=0.3,0.1

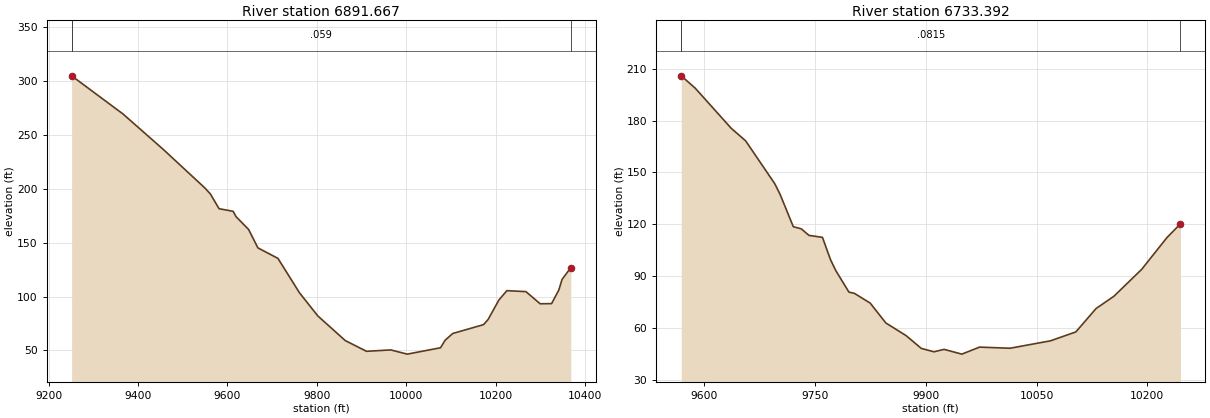
Type RM Length L Ch R = 1 ,6891.667,158.274900,158.274900,158.274900
XS GIS Cut Line= 6
1194493.52295614838771.7941232131194123.52693003838624.089973014
1193934.00594009838565.328872566 1193671.8453295838498.657446159
1193587.15013431838470.6668489031193441.03151619838405.455797358
#Sta/Elev= 30
9251.571305.09569366.429269.68439456.183236.92739550.055200.7997 9562.17195.2906
9581.421 181.6929612.786179.27079619.756174.16039647.636162.35799668.363145.2877
9713.216135.55069761.479103.50899802.49482.061849863.89659.172589911.37249.21671
9965.63150.5215310002.5246.6043210076.9552.5212710087.1759.4741210104.2265.77452
10173.1273.9833210183.4878.8268910207.6796.9465210225.39105.543710267.96104.6769
10299.8993.3738610325.4293.5120810341.54106.040810348.91116.017610368.46126.9411
#Mann= 3 , 0 , 0
9251.571   0.059       09251.571   0.059       010368.46   0.059       0
#XS Ineff= 2 , 0
       09896.595                       0
Bank Sta=9251.571,10368.46
Exp/Cntr=0.3,0.1

Type RM Length L Ch R = 1 ,6733.392,140.297800,140.297800,140.297800
XS GIS Cut Line= 3
1194228.48659405 838533.560467021193980.89853394838423.760544717
1193593.36939642838305.348863825
#Sta/Elev= 30
9568.806205.78589587.767198.62889636.513175.48859655.958 168.2769695.437143.5343
9702.615137.4131 9720.56118.70889731.327117.4782 9741.72113.70559760.039112.5482
9770.806 99.83039777.98393.443139795.92880.946419803.106 80.2878 9824.6474.63432
9845.88663.147669873.331 55.84139893.91448.471319911.06746.517619924.78947.91553
9948.80345.167589972.81749.2229910013.9848.5598410068.8752.8505810103.1857.98226
10130.6271.5066510154.6478.5367310192.3794.1073310226.68112.486810244.86120.3723
#Mann= 3 , 0 , 0
9568.806  0.0815       09568.806  0.0815       010244.86  0.0815       0
#XS Ineff= 2 , 0
       09932.009                       0
Bank Sta=9568.806,10244.86
Exp/Cntr=0.3,0.1