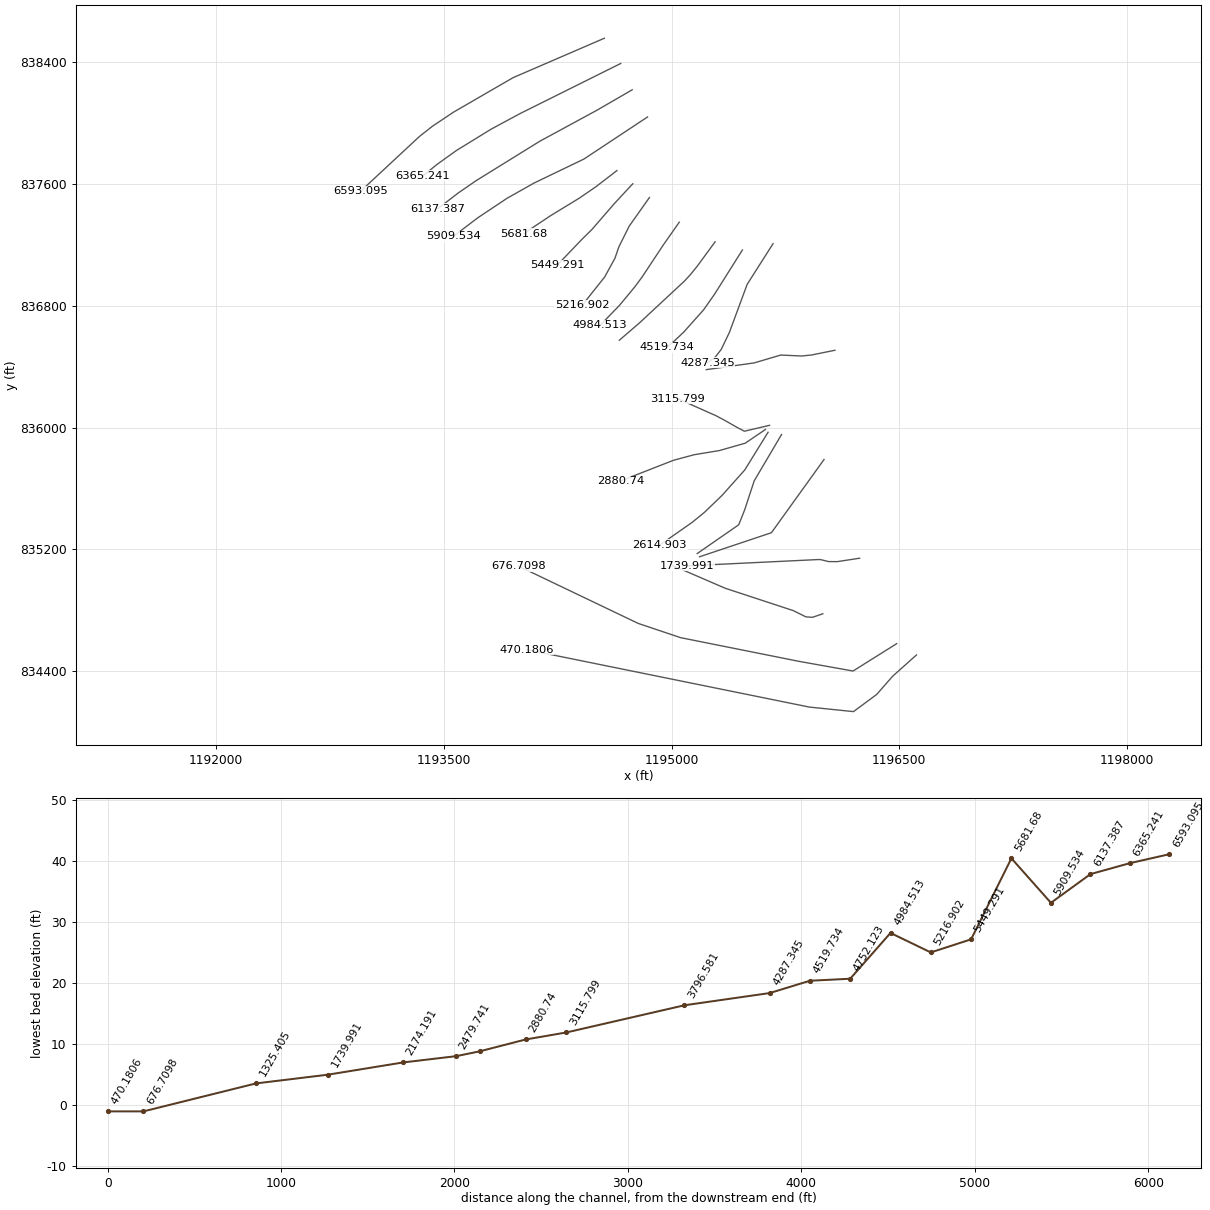
HEC-RAS study 109_ras.prj: 109

--- 109_ras.g01 (geometry) --- (continued)

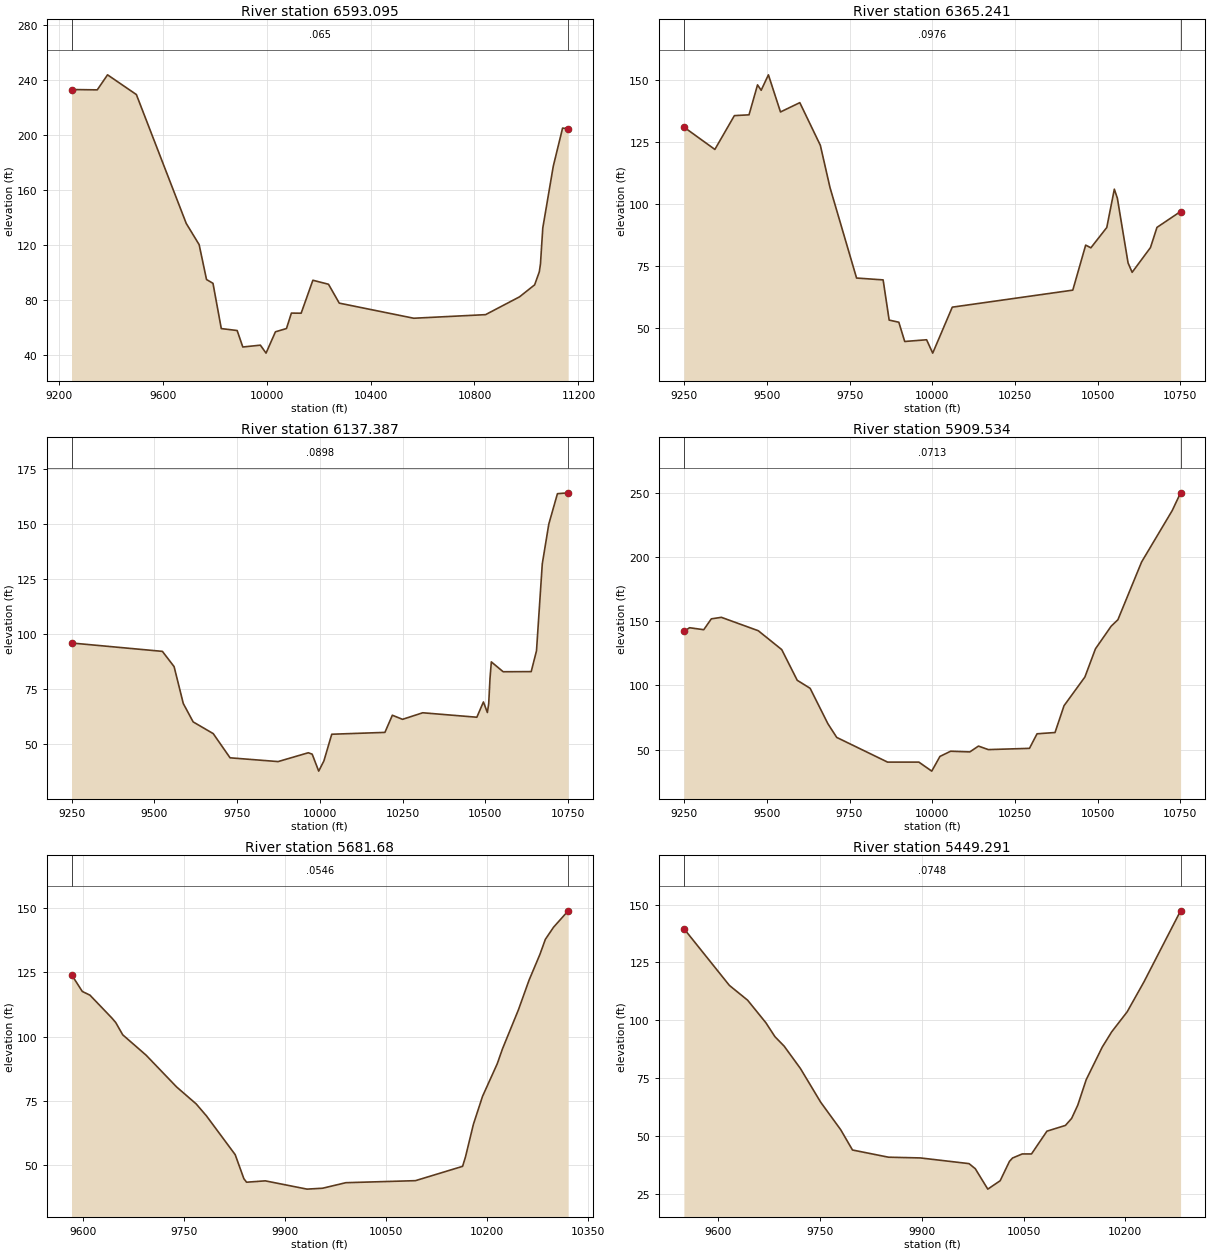
Type RM Length L Ch R = 1 ,6593.095,227.853600,227.853600,227.853600
XS GIS Cut Line= 6
1194557.38034257838555.3914920541193956.33490136 838296.74767372
1193562.43015328838069.4170560991193424.48115826837977.417347461
1193338.06268668837909.574218363  1192951.944538837551.525275186
#Sta/Elev= 30
9249.036233.07359348.139232.82799387.737243.78169498.748229.40669690.561135.5932
 9740.29120.11099768.70794.702979793.57291.94729 9825.5458.980779886.59657.57001
9908.37745.570319976.06746.896119997.78941.1060810033.8956.6191410076.4359.02184
10095.3170.2538810132.9270.1832910178.0494.1758710238.2191.2544210279.5777.51188
10566.31 66.511510842.5569.1221410973.4482.1025611031.58 90.850111049.47100.2998
11053.94106.006211062.88132.228811103.27177.230711139.07204.991911160.68204.4871
#Mann= 3 , 0 , 0
9249.036   0.065       09249.036   0.065       011160.68   0.065       0
#XS Ineff= 2 , 0
       09900.815        10131.01       0
Bank Sta=9249.036,11160.68
Exp/Cntr=0.3,0.1

Type RM Length L Ch R = 1 ,6365.241,227.853700,227.853700,227.853700
XS GIS Cut Line= 6
1194665.25588732838389.7138631791194006.08632849838062.870966338
1193812.46929107837959.1769618511193581.85865983837817.854067217
1193455.33315254837727.2882548061193361.65868822837651.675912083
#Sta/Elev= 30
9249.015131.09669342.716122.04959401.715135.73299445.965136.04539471.759148.1752
9482.713145.98449504.622152.23279541.136137.20999599.558140.97229661.632123.7286
9690.843106.62929771.17370.019659851.50469.268369869.76153.001869898.97252.13977
9916.77944.347899982.95445.0438310001.4439.6391810060.6158.2362310425.0165.12388
10464.0183.3410710479.7382.2413510527.7690.4595710550.68105.966510559.78102.3377
10592.21 76.117710604.49 72.333210659.9182.34693 10679.690.5171610750.9696.93112
#Mann= 3 , 0 , 0
9249.015  0.0976       09249.015  0.0976       010750.96  0.0976       0
#XS Ineff= 2 , 0
       0                10072.52       0
Bank Sta=9249.015,10750.96
Exp/Cntr=0.3,0.1

Type RM Length L Ch R = 1 ,6137.387,227.853600,227.853600,227.853600
XS GIS Cut Line= 6
1194741.30903153  838217.06965381194507.32834285838082.084178391
1194132.67852677837879.5615374391193711.71830457837619.939402189
1193593.04543049837538.2602183011193460.49629858837436.537234706
#Sta/Elev= 30
9249.036 95.95069523.91392.152989559.24485.240059587.08968.48778 9616.9160.16407
9677.58754.852959728.50643.880459873.77142.172859965.06946.172199976.87245.52928
9996.54537.8421110012.3542.5144810035.9654.5721310196.7655.4069610219.2463.19588
10250.0361.3306210311.0864.3039610474.7262.2829710494.6469.2091510506.5964.42946
10510.5768.3928610514.5579.9909410518.5487.3792710554.38 82.913510639.1182.97608
10655.1492.44009 10672.6131.857110692.39149.933910718.44163.661710750.95164.0542
#Mann= 3 , 0 , 0
9249.036  0.0898       09249.036  0.0898       010750.95  0.0898       0
#XS Ineff= 2 , 0
       0                10039.39       0
Bank Sta=9249.036,10750.95
Exp/Cntr=0.3,0.1

Type RM Length L Ch R = 1 ,5909.534,227.853600,227.853600,227.853600
XS GIS Cut Line= 6
1194842.07030614838038.6210497351194422.98934969837762.359942814
1194094.21809386837604.7447806671193917.68086385837505.528202706
1193723.93492742 837376.908662161193564.72477664837256.292652814
#Sta/Elev= 30
9249.029  142.119266.273144.98399309.094143.44449331.957151.90449362.431153.0916
9473.964142.64619544.876127.9387 9591.75103.99159630.81297.738249684.47670.11902
9711.25459.429759864.99440.178769959.51240.187679998.51533.1459810023.3244.61781
10055.5848.6598210113.7348.1363110139.7452.6718810169.5349.9334110294.0450.90883
10316.89  62.26210371.2763.2619810398.4884.1492210461.65106.551410493.48128.5056
10541.23146.249710561.37151.190210633.06196.251910725.83236.436410750.95250.1954
#Mann= 3 , 0 , 0
9249.029  0.0713       09249.029  0.0713       010750.95  0.0713       0
#XS Ineff= 2 , 0
       0                10085.31       0
Bank Sta=9249.029,10750.95
Exp/Cntr=0.3,0.1

Type RM Length L Ch R = 1 , 5681.68,232.389100,232.389100,232.389100
XS GIS Cut Line= 6
1194640.33836596837686.6246783621194502.46093789837580.964584673
1194393.39456035837506.2309688451194205.36832212837391.903565369
1194074.88373753837305.2732489651194029.47000056837272.252268242
#Sta/Elev= 30
9582.267124.17139598.367117.58149609.693116.1522 9642.22 107.2479647.969105.4936
9658.483100.65769693.30292.695329738.636 80.29769767.67773.696919782.99269.01445
9825.719 53.88839838.67244.488629842.64943.125749870.48943.656199932.61340.42642
9955.69140.776129990.308 42.935910093.8343.7290310163.95 49.320210168.2653.00119
10180.0765.76302 10193.676.6313310215.5289.3736210223.2695.1675710246.99110.4159
10262.77121.958410278.93132.030110287.05137.924710299.22142.656510321.03149.0615
#Mann= 3 , 0 , 0
9582.267  0.0546       09582.267  0.0546       010321.03  0.0546       0
#XS Ineff= 2 , 0
       0                               0
Bank Sta=9582.267,10321.03
Exp/Cntr=0.3,0.1

Type RM Length L Ch R = 1 ,5449.291,232.389100,232.389100,232.389100
XS GIS Cut Line= 6
 1194745.2865395837600.1289309391194733.79103734837588.578499026
1194624.23702426837470.7628159331194474.59001738837298.750432926
 1194409.7439819837235.3185269641194245.99440481837064.749714167
#Sta/Elev= 30
9549.262139.60759616.341 115.1029643.221108.71419670.10299.003239683.54292.95702
9697.08988.882159721.17979.195849750.97364.676589780.47152.808849797.86544.05312
9850.94440.946579897.88440.632189969.65438.17814 9978.8935.98706 9997.3627.16787
10015.5930.78605 10029.339.1491410033.8740.5978910048.1642.35011 10061.842.35855
10084.5452.1783210111.8354.6640310120.9357.6745210130.0263.4019310142.4174.37933
 10166.188.4637210180.0595.0640810202.79103.671610227.68116.6613 10281.6147.2817
#Mann= 3 , 0 , 0
9549.262  0.0748       09549.262  0.0748       0 10281.6  0.0748       0
#XS Ineff= 2 , 0
       0                               0
Bank Sta=9549.262,10281.6
Exp/Cntr=0.3,0.1

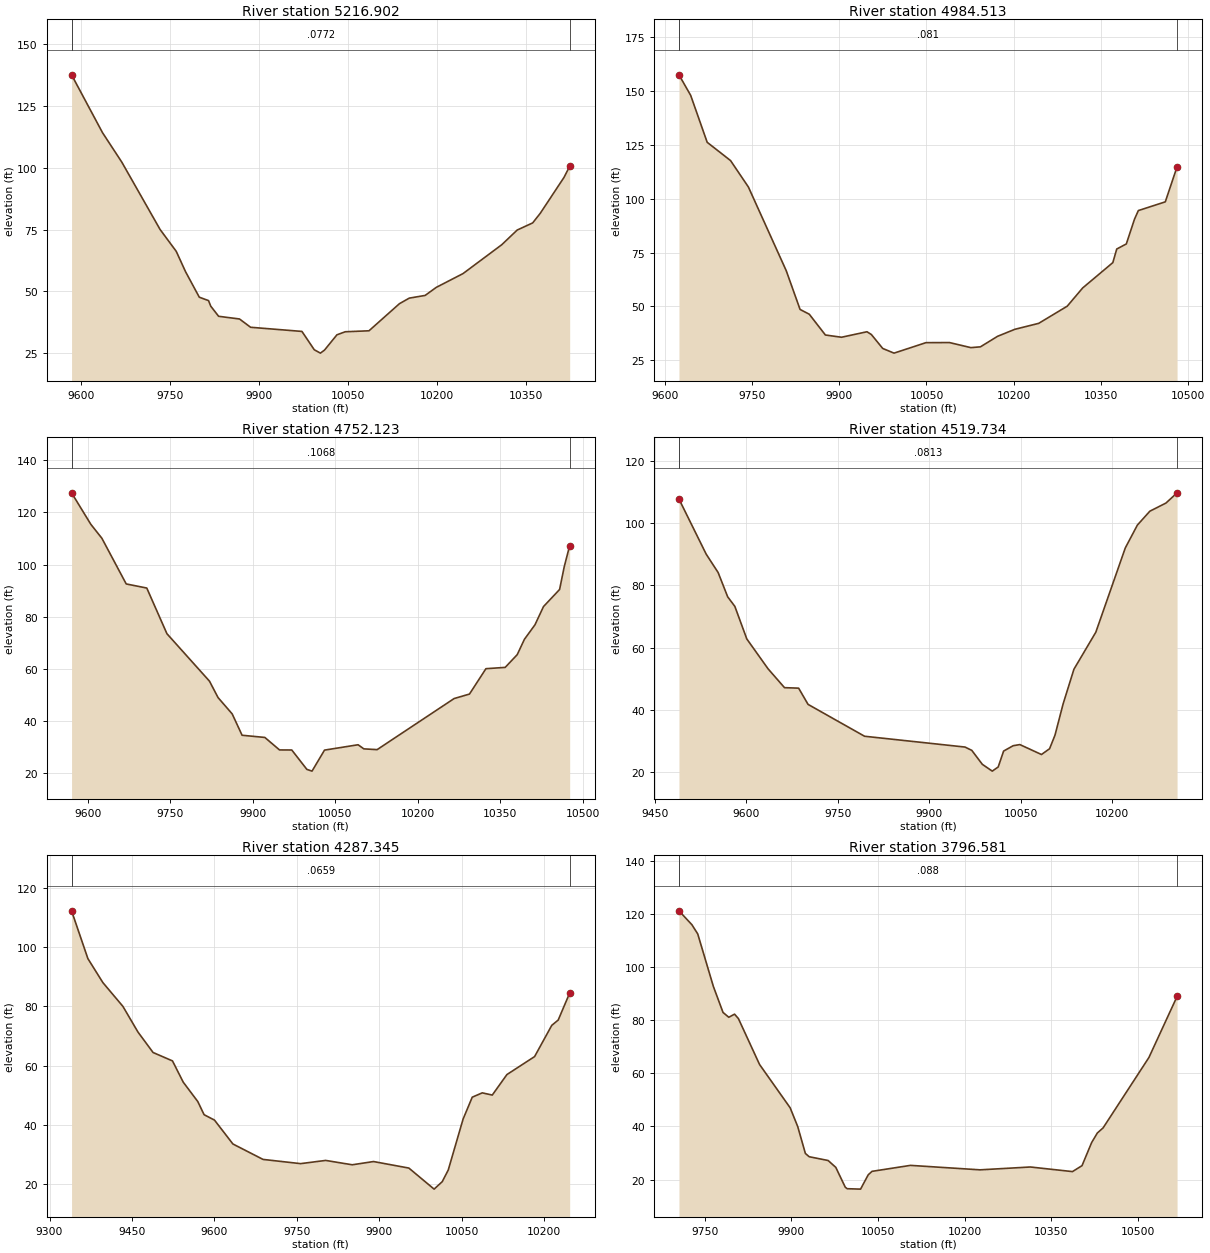
Type RM Length L Ch R = 1 ,5216.902,232.389100,232.389100,232.389100
XS GIS Cut Line= 6
1194854.61817583837510.0204394691194721.20245891837321.631912306
1194653.49838137837186.5838304911194627.37185136837111.233074534
1194559.53269278836988.0376997331194411.72441034836802.859976468
#Sta/Elev= 30
9583.297137.59479635.491 114.1939668.017102.27799732.59475.027679759.81166.19786
9775.36358.031439798.691 47.64519814.24346.273299817.98244.028289831.28139.92299
9866.52938.83192  9885.235.480239971.78833.801899992.58826.3842910002.9425.02291
10009.9126.27323 10030.832.4327710044.7333.6609210084.8634.05732 10136.245.01726
10152.7347.2677910179.5148.3629410198.4751.6404810243.48  57.20310308.7868.87775
10334.8674.8224510360.8577.6913910373.6281.56107 10413.796.0968510423.28100.5946
#Mann= 3 , 0 , 0
9583.297  0.0772       09583.297  0.0772       010423.28  0.0772       0
#XS Ineff= 2 , 0
       0                               0
Bank Sta=9583.297,10423.28
Exp/Cntr=0.3,0.1

Type RM Length L Ch R = 1 ,4984.513,232.389200,232.389200,232.389200
XS GIS Cut Line= 6
1195051.28791693837347.9299935151194948.17931225837201.634589709
1194806.14069335836987.8547287211194758.39938531836923.509458791
1194656.64453181836801.2286868021194529.85362723836671.114624206
#Sta/Elev= 30
9624.321157.63679644.507148.06069672.849126.25619713.022117.76659743.744105.4586
9808.83166.526039832.59348.527939848.43446.303219876.15636.639029903.87735.59841
9947.68138.152679955.26736.842459974.72430.385049994.18128.2109910049.1133.08195
10089.5533.1198210126.3230.7671410142.7331.1320210172.2136.0275410201.87 39.2779
10242.9742.0587710292.0750.0458910318.6258.5227110370.4570.30081 10377.276.62678
10393.6678.9865710407.5890.4001610414.3194.50437 10460.798.5690610480.94114.8843
#Mann= 3 , 0 , 0
9624.321   0.081       09624.321   0.081       010480.94   0.081       0
#XS Ineff= 2 , 0
       0                               0
Bank Sta=9624.321,10480.94
Exp/Cntr=0.3,0.1

Type RM Length L Ch R = 1 ,4752.123,232.389100,232.389100,232.389100
XS GIS Cut Line= 6
1195287.13879902837218.6976614211195169.76579333837059.188260611
1195126.00941972837005.4923022461195086.25629208836962.165973618
1194789.53187874836687.1921880881194656.31121771836572.928806332
#Sta/Elev= 30
9570.161 127.5069605.173115.43349625.302110.07189669.58792.543049707.00690.97104
9743.66673.447029821.10155.236919836.68248.936549862.44742.660159880.40834.48066
9921.79933.644279948.52528.849069970.79628.827479998.24621.3893710007.6620.71846
10030.3528.7794110091.4430.8359310101.9229.2633910126.0828.9643210266.25 48.5754
10294.1350.2887510324.0660.0270710359.0960.5215610380.9865.4086810394.1271.31158
10413.3276.88043 10428.883.8596310458.0890.4161110466.5899.1992110476.43107.2378
#Mann= 3 , 0 , 0
9570.161  0.1068       09570.161  0.1068       010476.43  0.1068       0
#XS Ineff= 2 , 0
       0                               0
Bank Sta=9570.161,10476.43
Exp/Cntr=0.3,0.1

Type RM Length L Ch R = 1 ,4519.734,232.389100,232.389100,232.389100
XS GIS Cut Line= 6
1195467.06286932 837165.279791631195284.00485672836875.821020707
1195211.36579505836772.3877170881195080.33759997836626.089679073
1195011.74059241836561.9377296331194966.72987898836526.522055084
#Sta/Elev= 30
9489.506 107.6759534.12190.001639553.70584.105659569.37276.307699581.12273.24307
9600.70662.798639635.52853.223259662.54447.161249685.70147.005599701.13941.80036
9793.76631.575569958.47628.107039969.55227.050129986.85922.5671910003.14 20.3859
10012.8921.7267110021.7626.8263310037.4528.5429310048.3528.9044710083.8225.71369
10097.1227.5742910105.9831.9261610119.2841.9394110137.01 53.070610172.9264.95443
 10221.291.9746410240.9999.30395 10261.5103.779510287.91 106.38810306.12109.6694
#Mann= 3 , 0 , 0
9489.506  0.0813       09489.506  0.0813       010306.12  0.0813       0
#XS Ineff= 2 , 0
       0                               0
Bank Sta=9489.506,10306.12
Exp/Cntr=0.3,0.1

Type RM Length L Ch R = 1 ,4287.345,490.763800,490.763800,490.763800
XS GIS Cut Line= 6
1195669.01811278837206.8277078221195498.48684692 836939.66065804
1195380.80776541836622.6710990061195327.24239752836512.136408662
1195285.65107149 836458.808531831195236.58899198836425.850468072
#Sta/Elev= 30
 9340.06112.2226 9369.7696.101079396.95588.030219433.43179.99664 9460.81 71.3462
9488.32164.440199523.60861.610459543.137 54.44699569.694 47.88479581.07643.47415
9600.04541.638639633.50233.592019688.29528.386469756.59326.96404 9802.2328.04754
9850.55726.576559889.21227.668979953.54625.46979 9999.4518.3681810014.2320.88773
10025.1524.8158510052.1241.9804210068.8249.3769810087.0250.8362810105.2250.09037
 10131.856.99537 10182.263.0666610213.4373.5993910225.1475.38695   1024684.50469
#Mann= 3 , 0 , 0
 9340.06  0.0659       0 9340.06  0.0659       0   10246  0.0659       0
#XS Ineff= 2 , 0
       0                               0
Bank Sta=9340.06,10246
Exp/Cntr=0.3,0.1

Type RM Length L Ch R = 1 ,3796.581,680.782400,680.782400,680.782400
XS GIS Cut Line= 6
1196076.73214692 836507.171197361195922.00099516836475.907383095
1195857.96004438836469.4772293521195719.85570027836475.635222951
  1195545.050839836424.1415133521195229.31036896 836379.93727869
#Sta/Elev= 30
9705.231121.22449727.592115.9993 9737.71 112.5329764.69392.798219781.49282.94178
 9791.4881.127619801.46882.287449808.12680.633219844.74863.328929897.68247.02889
9910.87239.911419924.061 29.8146 9930.6428.580589963.44827.155979976.69724.57617
9993.11317.097719996.42216.5309110019.6116.3734910032.8421.7634810039.4223.07195
10105.9925.3223810226.3523.6403310313.5224.71223 10386.422.9753410402.9625.21649
10419.5333.8813610429.47 37.524910439.4139.4353610518.77 65.9693 10567.588.95701
#Mann= 3 , 0 , 0
9705.231   0.088       09705.231   0.088       0 10567.5   0.088       0
#XS Ineff= 2 , 0
       0                               0
Bank Sta=9705.231,10567.5
Exp/Cntr=0.3,0.1

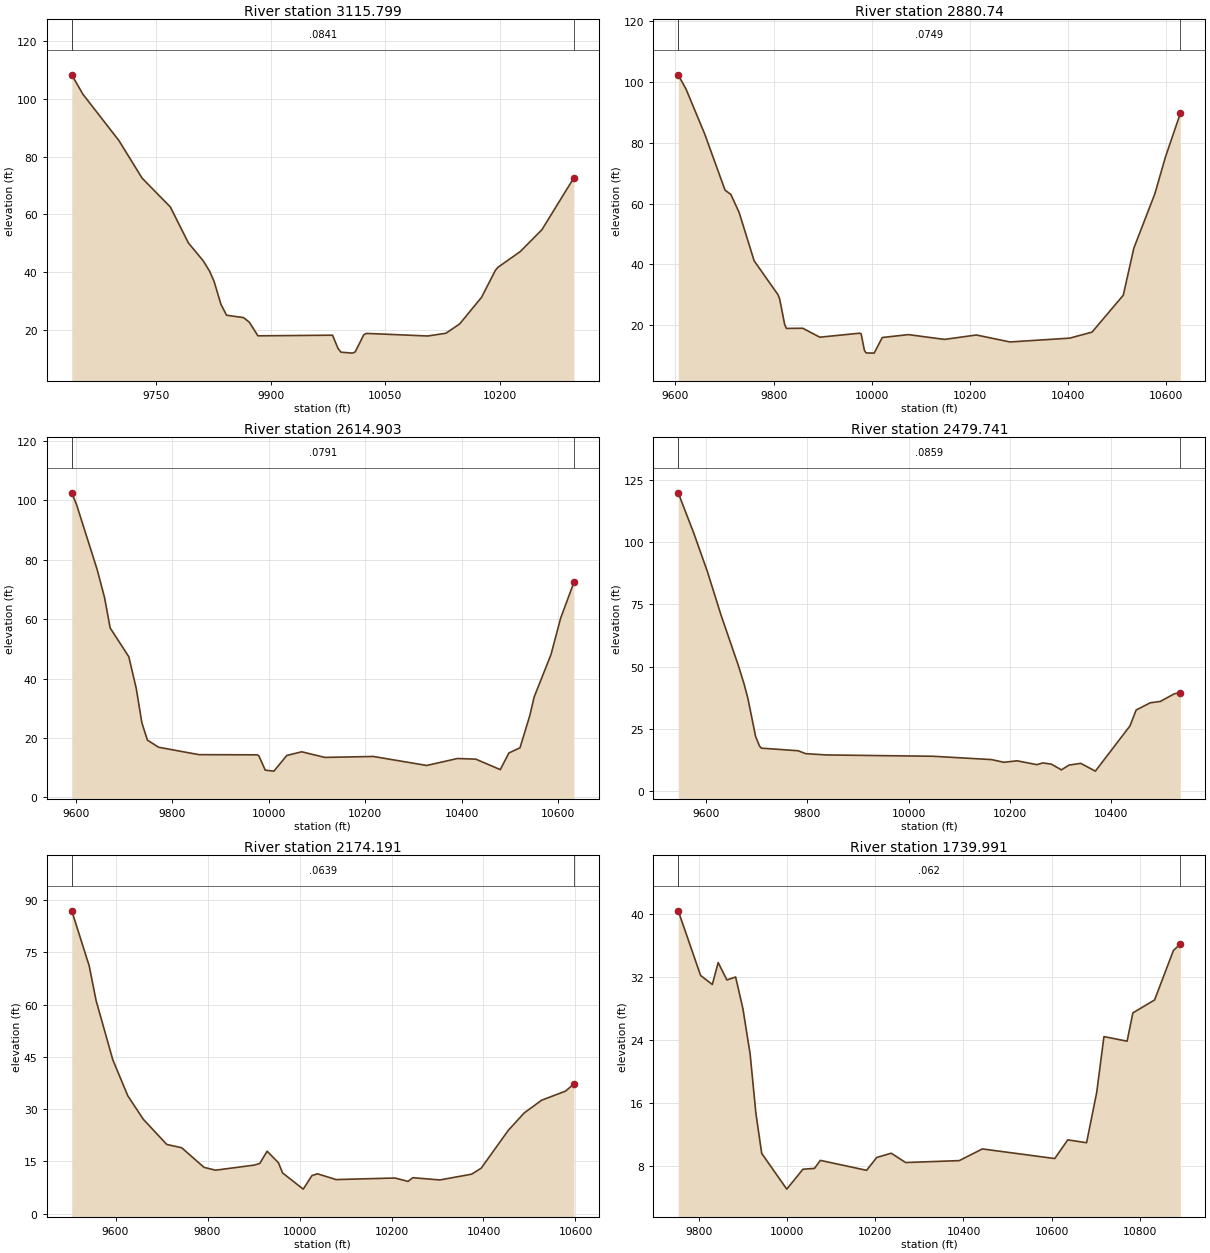
Type RM Length L Ch R = 1 ,3115.799,235.059200,235.059200,235.059200
XS GIS Cut Line= 6
1195645.95049587836014.4385956231195480.21085658835975.668418463
1195434.99199065835999.1106304841195352.76305104836045.807855448
1195293.27805217836077.4023031391195042.27386945836188.834065467
#Sta/Elev= 30
9639.106108.30739653.686101.59839700.85885.549359731.18272.551589768.24662.53559
9791.83250.104329811.32143.892619819.70340.276819825.57836.737219834.48528.83967
9841.87625.054099864.129 24.22339871.67422.644599882.99317.915049980.68118.13496
9988.10913.426189991.82312.2527210006.6811.9241310010.3912.3402910021.5518.25661
10025.1618.7575710105.3717.8572110129.2418.8101210147.1922.0301110175.9131.25422
10193.8640.5199610197.4541.6618610226.5747.0930610254.8954.63475 10296.872.62065
#Mann= 3 , 0 , 0
9639.106  0.0841       09639.106  0.0841       0 10296.8  0.0841       0
#XS Ineff= 2 , 0
       0                               0
Bank Sta=9639.106,10296.8
Exp/Cntr=0.3,0.1

Type RM Length L Ch R = 1 , 2880.74,265.836800,265.836800,265.836800
XS GIS Cut Line= 6
1195618.90843883835987.1285578161195485.86199811835897.087027222
1195315.88944006835848.7830534271195149.47814098835821.400471335
1195013.12005386835784.8262009971194662.79874918835648.346689522
#Sta/Elev= 30
9605.653 102.4249621.83597.623249659.57982.953469701.06664.45213 9712.95 63.0314
9729.82257.090099760.48941.148789809.04830.014099812.45828.573439822.69120.17743
9826.10118.91544 9859.5318.964039894.31616.019059975.244 17.33369978.55917.12082
9985.18911.689639988.50410.8414910005.0810.7716310021.6215.9191510074.9516.86295
 10148.4 15.292710213.4716.7450910282.0214.4491110403.5915.7081710449.2717.69253
10512.9729.8555610534.4545.3218410577.4263.30156 10598.975.3575210629.2289.69768
#Mann= 3 , 0 , 0
9605.653  0.0749       09605.653  0.0749       010629.22  0.0749       0
#XS Ineff= 2 , 0
       0                               0
Bank Sta=9605.653,10629.22
Exp/Cntr=0.3,0.1

Type RM Length L Ch R = 1 ,2614.903,135.162300,135.162300,135.162300
XS GIS Cut Line= 6
1195636.19103837835968.7382170861195482.49066541835721.073144376
1195333.14913258835554.4759816231195217.76629642835443.696346223
1195136.51957706835377.6796463131194923.00504437835228.712802726
#Sta/Elev= 30
9591.896102.57479601.96398.536749644.43776.765939659.88267.248499671.46657.05229
9710.07947.366729725.52436.663259737.192 25.09089748.69219.261669771.85916.87193
9855.40814.375999975.85914.312779979.57613.985459992.831 9.1529210010.728.826313
10037.4214.0937510068.2315.3405710116.4813.4442710216.7613.7653510327.3610.73412
10390.9513.0772810429.0412.8623310479.799.33731910497.6914.9439610520.6516.68485
10541.3227.7313510549.8333.7210710584.85 48.083510604.7960.3005310632.2372.37015
#Mann= 3 , 0 , 0
9591.896  0.0791       09591.896  0.0791       010632.23  0.0791       0
#XS Ineff= 2 , 0
       0                               0
Bank Sta=9591.896,10632.23
Exp/Cntr=0.3,0.1

Type RM Length L Ch R = 1 ,2479.741,305.549500,305.549500,305.549500
XS GIS Cut Line= 5
 1195725.0672659835953.8558122981195544.94573817 835650.03636785
1195482.01171035835459.0641456411195442.94921038835361.407895626
1195169.51171035835172.605812312
#Sta/Elev= 30
9545.086119.86329575.868103.62079602.56788.307949629.26570.95828 9663.7350.54403
9675.03443.150349682.66237.280759697.91921.999489705.54718.136429709.36117.27214
9781.82816.229399797.08515.049099837.43114.5450710048.4414.0110910163.8812.67757
10188.6111.5905910214.3212.1845310253.5810.6398910265.1211.3346610282.0910.85088
10302.038.54261910317.0910.4803310340.1911.1636210369.068.04005910437.5826.26873
10449.5432.5794410477.4535.5012110497.3936.04623 10525.339.1407310536.8339.55941
#Mann= 3 , 0 , 0
9545.086  0.0859       09545.086  0.0859       010536.83  0.0859       0
#XS Ineff= 2 , 0
       0                               0
Bank Sta=9545.086,10536.83
Exp/Cntr=0.3,0.1

Type RM Length L Ch R = 1 ,2174.191,434.200400,434.200400,434.200400
XS GIS Cut Line= 3
1196004.93270335835789.8147346381195658.32560673835309.369254187
1195184.74363312835151.508596331
#Sta/Elev= 30
9504.82986.960039542.65371.194569557.70861.195559594.11744.142539626.76733.80501
9660.41327.070929711.43619.84311  9743.818.901079792.346 13.27149817.42612.45269
9901.57513.916489913.711 14.40559929.57817.911399954.16614.598559963.22411.66247
10008.097.01358110026.9810.8986410039.1211.4141410079.58 9.7580510207.5510.20844
10235.939.232766 10246.310.2961910305.09 9.6492410374.2611.3069110395.0113.03461
 10453.823.8780110488.3828.8822310526.4232.56219 10578.335.1652910596.4537.21115
#Mann= 3 , 0 , 0
9504.829  0.0639       09504.829  0.0639       010596.45  0.0639       0
#XS Ineff= 2 , 0
       0                               0
Bank Sta=9504.829,10596.45
Exp/Cntr=0.3,0.1

Type RM Length L Ch R = 1 ,1739.991,414.585800,414.585800,414.585800
XS GIS Cut Line= 6
1196239.22740185835141.9918059061196092.49602953835119.502761705
  1196034.801708835119.8938126091195981.52681507835133.035173365
1195964.05504581835133.0624136031195104.30049554835091.760189027
#Sta/Elev= 30
9752.56940.467359803.329 32.23189829.95331.083329843.20833.871769863.06531.65857
9882.83332.037889899.30728.022789915.72622.238869928.85614.665619941.9929.568641
9998.8775.00680410035.597.54134110061.877.64667910075.018.67040910180.117.404671
10203.119.04226310235.95 9.58201 10268.88.39531510390.33 8.6381210442.88 10.1295
10607.128.90212610636.6811.2834210679.3810.9195810702.3717.3313410718.79 24.4407
10771.3523.8555910784.4827.4621710833.7529.1125610876.45  35.41210892.12 36.2369
#Mann= 3 , 0 , 0
9752.569   0.062       09752.569   0.062       010892.12   0.062       0
#XS Ineff= 2 , 0
       0                10637.11       0
Bank Sta=9752.569,10892.12
Exp/Cntr=0.3,0.1

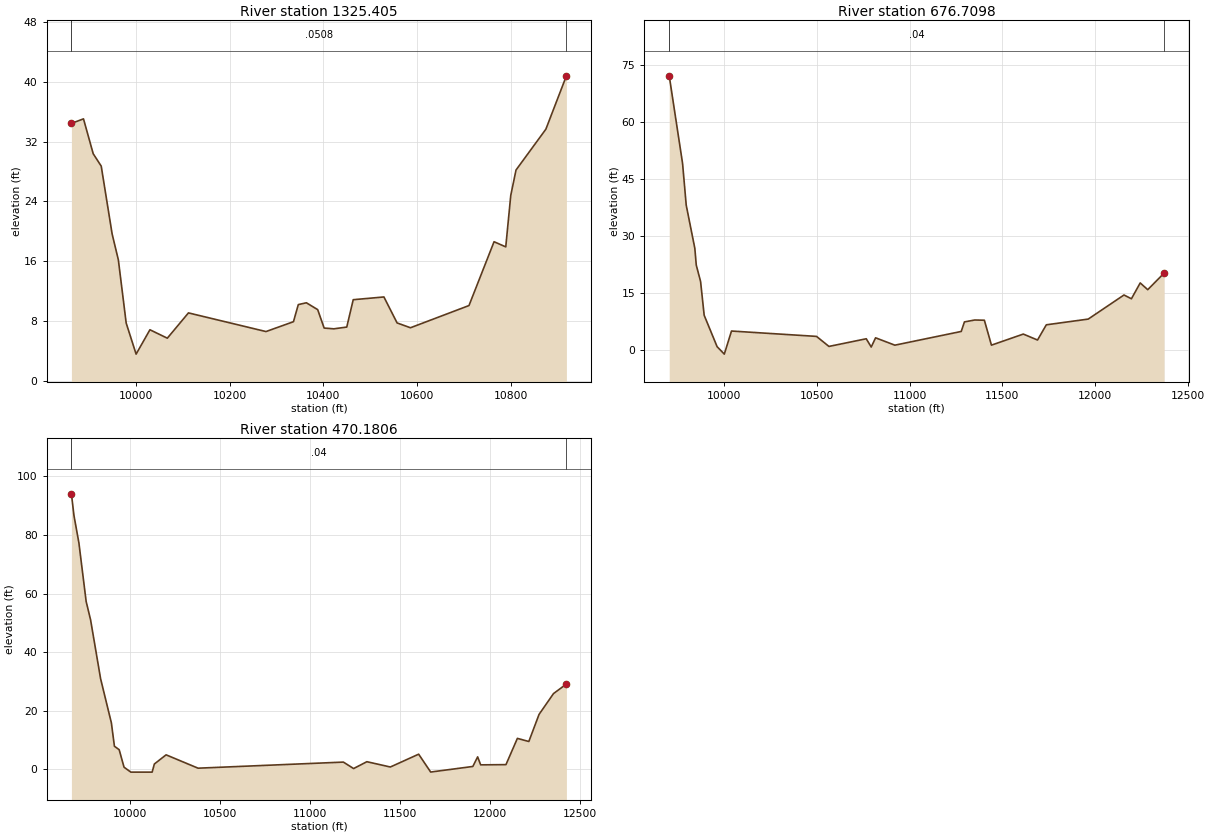
Type RM Length L Ch R = 1 ,1325.405,648.695300,648.695300,648.695300
XS GIS Cut Line= 6
1195996.94247209834777.2912092831195928.89275522834753.954420603
1195885.55581308834756.9446619231195802.58349074834797.922538496
1195355.22117615834944.2892626821195007.45391706835093.961247623
#Sta/Elev= 30
 9861.7334.447629887.53935.056679908.31530.390259925.42328.735919948.75919.64795
9962.022 16.19329978.7627.7370449999.9673.576192 10029.56.83806410066.695.709061
10111.819.09309910277.516.59630810336.197.91495110346.55 10.201810363.8110.44709
10387.979.53091710401.787.06421210422.496.960776 10450.17.19920810463.9110.85897
 10529.511.2260610557.687.74923610586.257.10594210711.2710.0761110764.8418.61579
10789.85 17.927710800.5624.8259210811.7828.2119910875.5733.6754210919.4640.81624
#Mann= 3 , 0 , 0
 9861.73  0.0508       0 9861.73  0.0508       010919.46  0.0508       0
#XS Ineff= 2 , 0
       0                10494.77       0
Bank Sta=9861.73,10919.46
Exp/Cntr=0.3,0.1

Type RM Length L Ch R = 1 ,676.7098,206.529200,206.529200,206.529200
XS GIS Cut Line= 6
1196483.53661999834580.9498526751196196.09049946 834401.41294466
1195837.90698057834465.2719176411195060.25980842834620.358696967
1194781.25191477834713.6912598161193992.76590151835089.559130415
#Sta/Elev= 30
9707.12472.073059779.01649.063069798.50638.133739844.92526.788289852.66122.37441
9875.871 18.07659895.212 9.200019964.8390.95428110003.52  -0.999 10042.25.064698
10499.643.65697710566.551.02175210767.28 3.0352810794.040.86761210817.463.285848
10921.171.35265811278.274.95422711295.57  7.459311350.927.96054111402.817.902533
11440.871.35845511612.494.26664311688.812.70018411736.066.698546 11961.68.200673
12154.03 14.528512194.0113.5345312241.2617.6940612281.8315.9229412370.5220.30466
#Mann= 3 , 0 , 0
9707.124    0.04       09707.124    0.04       012370.52    0.04       0
#XS Ineff= 2 , 0
       0                10873.42       0
Bank Sta=9707.124,12370.52
Exp/Cntr=0.3,0.1

Type RM Length L Ch R = 1 ,470.1806,0.000000,0.000000,0.000000
XS GIS Cut Line= 6
1196613.85703501834506.7351622111196456.46337727834366.685040846
 1196352.1524103834247.9180546251196199.16814208834134.917740673
1195908.06601503834164.7743690911194045.75881773834541.714302823
#Sta/Elev= 30
9672.58794.06939 9686.7186.677529714.23277.306129754.49757.30268 9779.2950.97617
9834.92230.883499894.79115.825529911.6617.8429399938.0656.6627529965.2260.680764
10002.95  -0.99910121.38  -0.99910133.621.76874410198.884.90829310376.660.348752
11184.522.42662311241.42 0.2190111315.062.56043711445.61 0.7509311602.945.128985
11669.88-0.97162 11904.20.93839911930.984.21436911947.711.485816 12088.31.558465
 12151.910.52782 12215.59.46291212272.4118.7330112352.7525.8371112424.4229.08912
#Mann= 3 , 0 , 0
9672.587    0.04       09672.587    0.04       012424.42    0.04       0
#XS Ineff= 2 , 0
       0                11203.81       0
Bank Sta=9672.587,12424.42
Exp/Cntr=0.3,0.1